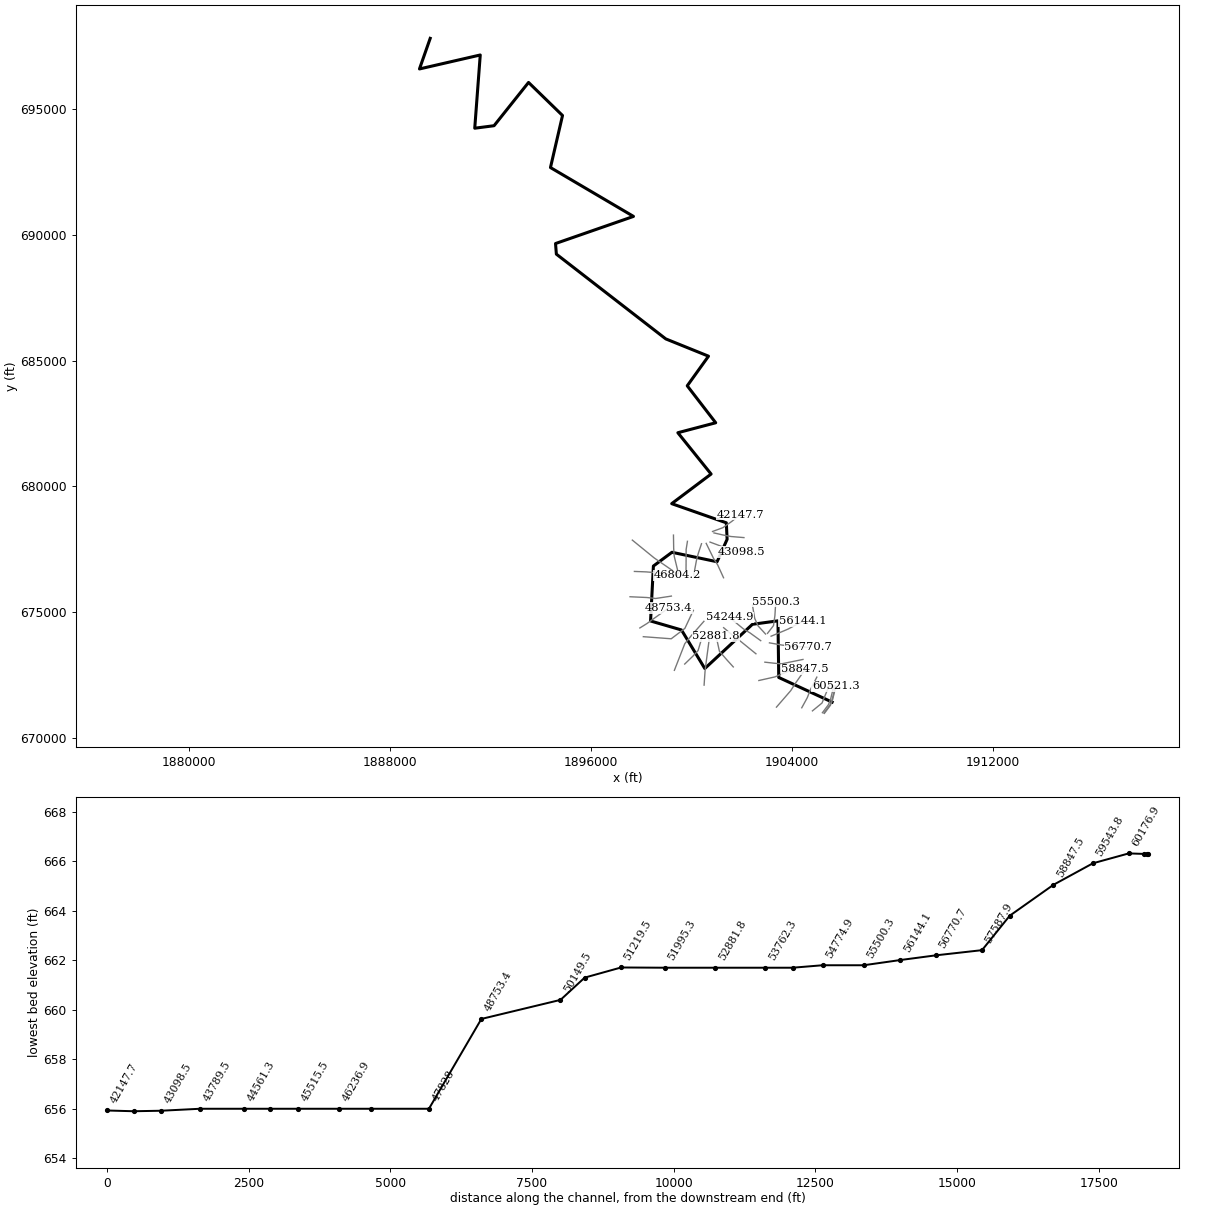
--- LtlKwhaRvr.prj (project) ---

Proj Title=LtlKwhaRvr
Current Plan=p01
Default Exp/Contr=0,0
English Units
Geom File=g01
Flow File=f01
Plan File=p01
BEGIN DESCRIPTION:
AMEC Environment & Infrastructure, 2013
Projection: NAD 1983 State Plane West Virginia South FIPS 4702 (US Feet)
Vertical Datum: NAVD 1988
END DESCRIPTION:
DSS Export Rating Curves= 0
DSS Export Rating Curve Sorted= 0
DSS Export Volume Flow Curves= 0
DXF OffsetX= 0
DXF OffsetY= 0
DXF ScaleX= 0
DXF ScaleY= 0

--- LtlKwhaRvr.p01 (plan) ---

Plan Title=Floodplain
Program Version=4.00
Geom File=g01
Flow File=f01
K Sum by GR=0
Std Step Tol=0.01
Critical Tol=0.01
Num of Std Step Trials=20
Max Error Tol=0.3
Flow Tol Ratio=0.001
Split Flow NTrial=30
Split Flow Tol=0.02
Split Flow Ratio=0.02
Log Output Level=0
Friction Slope Method=1
Unsteady Friction Slope Method=2
Unsteady Bridges Friction Slope Method=1
Global Log Level=0
CheckData=False
Run HTab=0
Run UNet=0
Run PostProcess=0
UNET Theta=0
UNET Theta Warmup=0
UNET ZTol=0
UNET ZSATol=0
UNET MxIter=0
UNET MaxInSteps=0
UNET DtIC=0
UNET DtMin=0
UNET MaxCRTS=0
UNET WFStab=0
UNET SFStab=0
UNET WFX=0
UNET SFX=0
UNET DSS MLevel=0
UNET DZMax Abort=0
UNET Convert EG Bridges=0
UNET Use Existing IB Tables=0
UNET Froude Limit=0
UNET Froude Power=0
Write IC File=0
Echo Input=False
Echo Output=False
Write Detailed=0

--- LtlKwhaRvr.f01 (steady flow) ---

Flow Title=NFF Regression Equation
Program Version=4.10
Number of Profiles= 1
Profile Names=P100yr
River Rch & RM=LtlKwhaRvr,Main            ,60521.3
20121.62
River Rch & RM=LtlKwhaRvr,Main            ,50576.4
   20203
River Rch & RM=LtlKwhaRvr,Main            ,50149.5
20669.05
River Rch & RM=LtlKwhaRvr,Main            ,30498.6
20920.65
River Rch & RM=LtlKwhaRvr,Main            ,29536.2
21526.05
River Rch & RM=LtlKwhaRvr,Main            ,16325.7
21863.86
River Rch & RM=LtlKwhaRvr,Main            ,15816.3
21935.06
River Rch & RM=LtlKwhaRvr,Main            ,717.8
22144.19
River Rch & RM=LtlKwhaRvr,Main            ,142.3
22149.89
Boundary for River Rch & Prof#=LtlKwhaRvr,Main            , 1
Up Type= 0
Dn Type= 3
Dn Slope=0.00068
DSS Import GetInterval= 0
DSS Import GetPeak= 0
DSS Import FillOption= 0

--- LtlKwhaRvr.g01 (geometry) ---

Geom Title=USGS 3m DEM
Program Version=4.10

River Reach=LtlKwhaRvr      ,Main
Reach XY= 30
     1905591.528      671414.576     1903468.197      672395.225
     1903437.797      674647.545     1902422.201      674510.063
     1900527.434      672750.629     1899599.933      674284.174
     1898370.275      674641.904     1898483.081      676826.786
     1899221.194      677373.903      1901015.31      676997.089
     1901414.737      677889.813      1901383.45      678546.318
      1899210.59      679308.224      1900777.42       680485.94
     1899455.472      682129.243     1900961.256      682525.292
     1899828.809      683995.643     1900674.581      685173.892
      1898974.23      685861.595     1894623.411      689232.535
     1894590.181       689654.28     1897691.705      690733.134
     1894388.791      692676.599     1894868.056       694746.89
     1893516.763       696061.59     1892144.766      694340.354
     1891377.104      694241.321     1891595.805      697153.952
     1889178.199      696598.059     1889605.528      697815.956

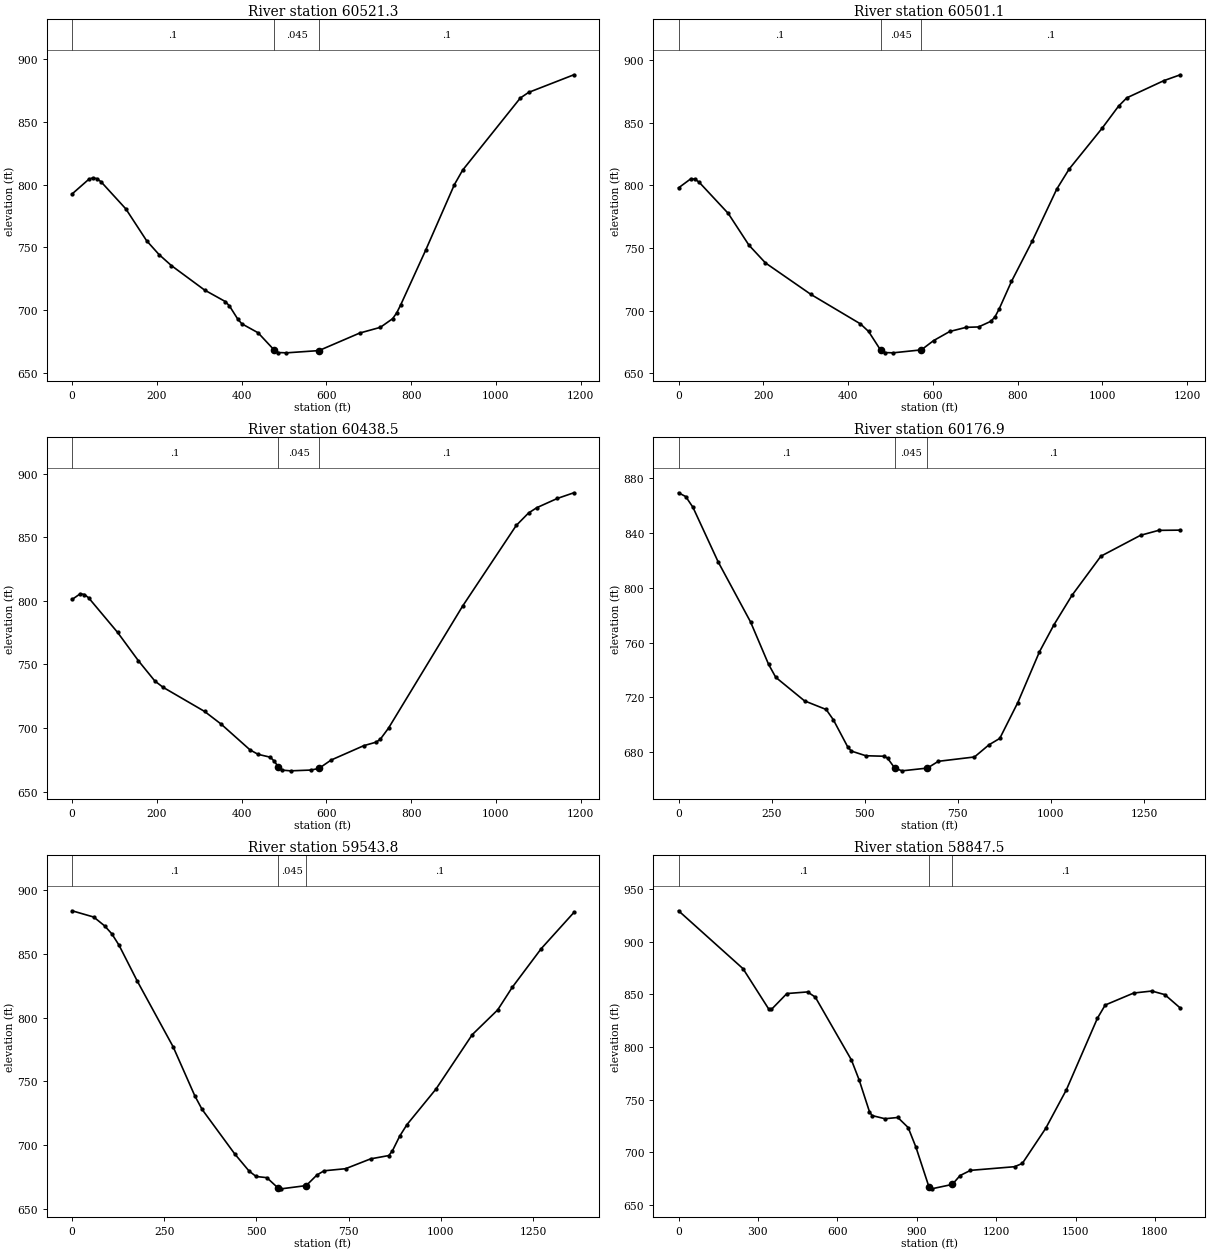
Type RM Length L Ch R = 1 ,60521.3 ,20.2,20.2,20.2
XS GIS Cut Line= 4
     1905283.068      670966.683      1905523.52      671286.995
     1905612.061      671519.634     1905738.798      672038.731
#Sta/Elev= 30
       0   792.5    39.1  804.06    48.8  805.32    58.6  804.68    68.4  802.18
     127  780.59   175.8   755.4   205.1   744.4   234.4   735.6   312.6  716.19
   361.4  707.07   371.2  703.61   390.8  693.16   400.5  689.37   438.8  682.25
   477.1  668.44   486.7  666.54   505.8   666.3   582.4  668.09   678.6  682.02
   727.2  686.55   756.3  693.44     766  698.14   775.7   704.7     834   747.7
     902  799.96   921.5  811.48  1057.5  868.74  1076.9  873.16  1183.8  887.19
#Mann= 3 , 0 , 0
       0      .1       0   477.1    .045       0   582.4      .1       0
Bank Sta=477.1,582.4
XS Rating Curve= 0 ,0
Exp/Cntr=0.3,0.1

Type RM Length L Ch R = 1 ,60501.1 ,62.6,62.5,62.5
XS GIS Cut Line= 4
     1905267.443      670982.308     1905507.895       671302.62
     1905596.436      671535.259     1905723.173      672054.356
#Sta/Elev= 30
       0  798.09    29.3  805.43    39.1  805.01    48.8  802.55   117.2   777.7
   166.1  752.32   205.1  738.12   312.6  712.91   429.2  689.42   448.4  683.36
   477.1  668.28   486.7  666.54   505.8   666.3   572.8  668.67   601.6  676.05
   639.9  683.37   678.6  686.68   707.7  686.98   736.9  691.49   746.6  695.08
   756.3  701.28   785.4  723.31     834  755.28   892.3  797.13   921.5  813.11
   999.2   845.7    1038  863.35  1057.5  870.01  1144.9  883.75  1183.8  888.44
#Mann= 3 , 0 , 0
       0      .1       0   477.1    .045       0   572.8      .1       0
Bank Sta=477.1,572.8
XS Rating Curve= 0 ,0
Exp/Cntr=0.3,0.1

Type RM Length L Ch R = 1 ,60438.5 ,262.3,261.7,261.1
XS GIS Cut Line= 4
     1905204.943      670992.724     1905445.395      671313.037
     1905533.936      671545.676     1905660.673      672064.773
#Sta/Elev= 30
       0  801.14    19.5  805.68    29.3  805.04    39.1  802.44   107.5   775.2
   156.3  753.01   195.4  736.95   214.9     732   312.6  713.05   351.7  703.06
   419.7  682.83   438.8  679.29   467.5  677.04   477.1   673.9   486.7  669.36
   496.3  666.85   515.4   666.3   563.3  666.91   582.4  668.21   611.1  674.79
   688.3  686.12   717.4  688.88   727.2  691.18   746.6  699.94   921.5  796.01
  1047.8  859.37  1076.9   869.2  1096.4  873.39  1144.9  880.67  1183.8  885.11
#Mann= 3 , 0 , 0
       0      .1       0   486.7    .045       0   582.4      .1       0
Bank Sta=486.7,582.4
XS Rating Curve= 0 ,0
Exp/Cntr=0.3,0.1

Type RM Length L Ch R = 1 ,60176.9 ,632.6,633.1,633.5
XS GIS Cut Line= 4
     1904808.242      671065.641     1905189.566      671378.394
     1905277.943      671594.766     1905515.707      672168.071
#Sta/Elev= 30
       0  869.35    19.3  866.58    38.7  858.75   106.4   818.9   193.4  775.05
   241.8   744.1   261.1   734.6   338.4   717.4   396.5  711.11   415.8  703.59
   454.5  683.72   464.2  680.74   502.9  677.35   551.6  676.98   561.4  675.54
   580.8  668.28   600.3  666.32   668.5  668.35   697.7  673.28   794.8  676.45
   833.6   685.3   862.7     690   911.2   716.2   969.3  753.25  1008.1  772.91
  1056.6  794.45  1134.2  823.03  1240.9  838.32  1289.4  841.91  1347.6  842.08
#Mann= 3 , 0 , 0
       0      .1       0   580.8    .045       0   668.5      .1       0
Bank Sta=580.8,668.5
XS Rating Curve= 0 ,0
Exp/Cntr=0.3,0.1

Type RM Length L Ch R = 1 ,59543.8 ,700.6,696.3,691.9
XS GIS Cut Line= 4
     1904383.763      671188.905     1904605.117      671592.551
     1904722.305       671900.71     1904982.721      672408.523
#Sta/Elev= 30
       0  883.57    58.8  878.66    88.2  871.78   107.7  865.58   127.3  856.65
   176.3   828.8   274.2  777.02     333  738.63   352.6  728.09   440.8  693.37
   479.8   679.9   499.1  675.58   528.2  674.67   557.3  666.91     567  665.92
   634.9  668.46     664  676.76   683.4  680.05   741.6  681.68   809.7  689.39
   858.9  691.98   868.8  695.74   888.4  707.16   908.1  716.18   986.8  744.02
  1085.2  786.62  1154.1  805.97  1193.5  823.61  1272.2  853.93  1360.7  882.23
#Mann= 3 , 0 , 0
       0      .1       0   557.3    .045       0   634.9      .1       0
Bank Sta=557.3,634.9
XS Rating Curve= 0 ,0
Exp/Cntr=0.3,0.1

Type RM Length L Ch R = 1 ,58847.5 ,785.3,771.7,758
XS GIS Cut Line= 4
     1903376.818      671214.946     1903945.395      671870.328
     1904123.346      672152.446     1904522.652      672721.023
#Sta/Elev= 30
       0  929.48   243.7  874.41   341.2  835.88     351  835.68   409.4  850.77
   487.4   852.3   516.7  847.39   653.2  787.63   682.4  768.65   721.4  738.41
   731.2  734.75   779.9  731.72   828.6  732.91   867.6  723.34   897.1  704.61
   946.1  667.01   955.9  665.05  1034.4  669.24  1063.8  677.69  1103.1  682.62
  1269.7  686.09    1299  689.22  1387.1  722.47  1465.4   759.2  1582.8  827.32
  1612.2  839.86  1719.8  851.26  1788.3  853.16  1837.3  849.75    1896  836.94
#Mann= 3 , 0 , 0
       0      .1       0   946.1    .045       0  1034.4      .1       0
Bank Sta=946.1,1034.4
XS Rating Curve= 0 ,0
Exp/Cntr=0.3,0.1

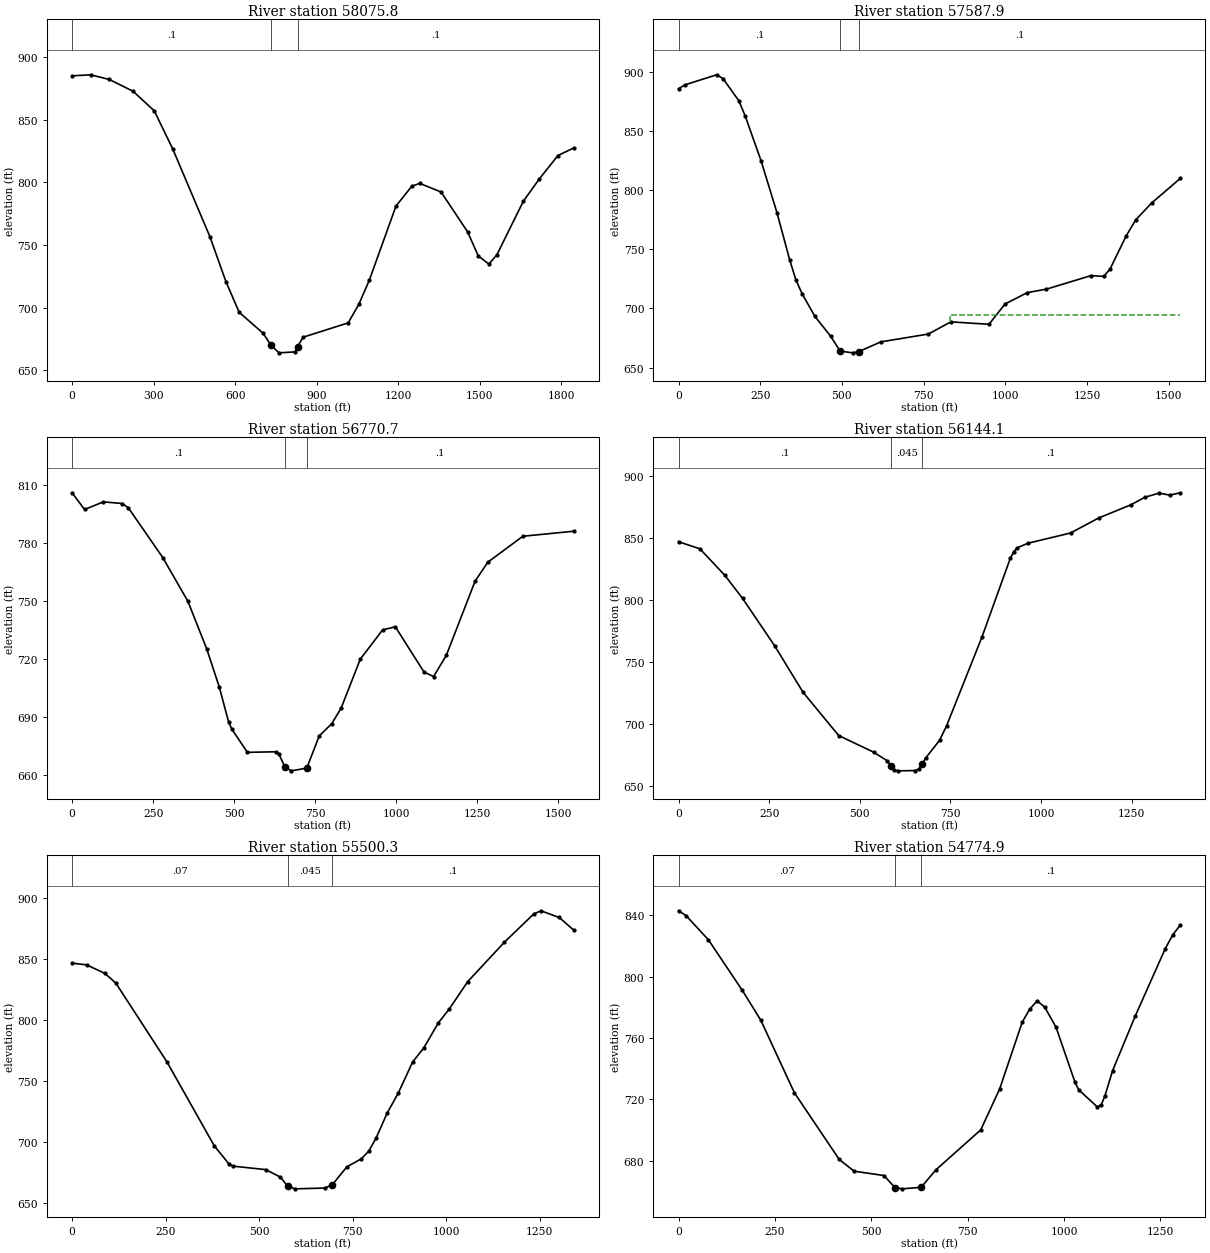
Type RM Length L Ch R = 1 ,58075.8 ,498.7,487.9,477.2
XS GIS Cut Line= 4
     1902678.034      672273.974     1903316.055      672417.203
      1903550.43       672517.03     1904418.485      672872.933
#Sta/Elev= 30
       0     885    68.3  885.86   136.6  882.14   224.5   872.7   302.6  857.06
   370.9  826.46   507.5  756.47   566.1  720.77   614.9   696.2   702.9   679.5
   732.3  669.78   761.7   663.8   820.5  664.56   830.3  668.83   849.9  676.26
  1016.2  687.72  1055.2  702.44  1094.3     722  1192.1     781  1250.7  796.95
    1280   799.1  1358.2  792.24  1455.9  760.36    1495  741.19  1534.1  734.68
  1563.4  742.08  1661.2     785  1719.8  802.72  1788.2  821.37  1846.8  827.48
#Mann= 3 , 0 , 0
       0      .1       0   732.3    .045       0   830.3      .1       0
Bank Sta=732.3,830.3
XS Rating Curve= 0 ,0
Exp/Cntr=0.3,0.1

Type RM Length L Ch R = 1 ,57587.9 ,818,817.2,816.1
XS GIS Cut Line= 4
     1902916.749      673003.141     1903303.034      672959.738
     1903580.811      672938.037     1904431.506      673111.648
#Sta/Elev= 30
       0  885.75    19.4  888.98   116.6  897.54     136  894.34   184.6  875.56
   204.1  862.63   252.7   824.7   301.2  780.97   340.1  741.06   359.6  723.74
     379  711.96   417.5  693.16   465.6  676.43   494.4  663.93   532.8  662.41
     552  663.52   619.3  671.69   764.9  678.33   833.2   688.6   950.2  686.56
     999  703.69  1067.3  713.35  1125.8  716.27  1262.4  727.73  1301.4  727.04
    1321  733.53  1369.7  761.18    1399  774.83  1447.8  789.12  1535.6  809.92
#Mann= 3 , 0 , 0
       0      .1       0   494.4    .045       0     552      .1       0
#XS Ineff= 2 , 0
                          832.11          694.73
Permanent Ineff=
       F       F
Bank Sta=494.4,552
XS Rating Curve= 0 ,0
Exp/Cntr=0.3,0.1

Type RM Length L Ch R = 1 ,56770.7 ,614.7,626.6,638.2
XS GIS Cut Line= 4
     1903099.041       673771.37     1903593.832      673684.565
     1903919.353      673645.502     1904635.499      673593.419
#Sta/Elev= 30
       0  805.88    38.6  797.24    96.6  801.18   154.6  800.34   173.9  798.06
   280.2   772.3   357.4   749.8   415.4  725.25     454  705.62     483  687.46
   492.7   683.8   540.9  671.76   627.7  672.05   637.4   671.1   656.6  664.27
   675.9   662.2   724.1   663.6   762.7  680.28   801.3  686.58   830.2  694.63
   889.2  719.88   958.1  735.02   997.4  736.64  1085.9  713.24  1115.4  710.92
  1154.8  721.92  1243.3  760.15  1282.7  770.02  1390.9  783.42  1548.2  786.02
#Mann= 3 , 0 , 0
       0      .1       0   656.6    .045       0   724.1      .1       0
Bank Sta=656.6,724.1
XS Rating Curve= 0 ,0
Exp/Cntr=0.3,0.1

Type RM Length L Ch R = 1 ,56144.1 ,620.6,643.8,667.1
XS GIS Cut Line= 4
     1903164.145      674036.127     1903580.811      674209.738
     1903845.568      674322.585     1904414.145      674626.405
#Sta/Elev= 30
       0  846.81    58.9  841.11   127.6  819.74   176.6  801.09     265  762.91
   343.4  725.36   441.6   690.5   537.7  677.11   576.1  670.04   585.7  666.16
   595.3  662.65   604.9  662.01   652.8  662.23   662.4  663.45     672  667.54
   681.6  672.36     720   686.7   739.2  698.34   836.9  770.06     915  833.52
   924.8  838.88   934.5  841.99   963.8  845.62  1081.1  853.87  1159.2  866.05
  1247.1  876.57  1286.2  882.72  1325.2  886.02  1354.6  884.43  1383.8  886.31
#Mann= 3 , 0 , 0
       0      .1       0   585.7    .045       0     672      .1       0
Bank Sta=585.7,672
XS Rating Curve= 0 ,0
Exp/Cntr=0.3,0.1

Type RM Length L Ch R = 1 ,55500.3 ,712.7,725.4,738.1
XS GIS Cut Line= 4
     1903020.916      674148.974     1903259.631      674457.134
     1903316.055       674856.44     1903350.777      675403.315
#Sta/Elev= 30
       0   846.7      39  845.28    87.7   838.3   116.9  830.39   253.4  765.88
   380.1     697   419.3  682.18   429.2  680.42   517.7  677.54     557  671.38
   576.7  663.72   596.4   661.8     675  662.44   694.7  664.91   734.1  679.74
   773.4   686.5   793.1  692.76   812.6  703.43     842  723.84   871.4  740.03
   910.5  765.93   939.9  777.19     979  797.86  1008.4  809.27  1057.3  831.54
  1155.1  863.76  1233.4  886.89    1253   889.6  1301.9   884.1    1341  873.67
#Mann= 3 , 0 , 0
       0     .07       0   576.7    .045       0   694.7      .1       0
Bank Sta=576.7,694.7
XS Rating Curve= 0 ,0
Exp/Cntr=0.3,0.1

Type RM Length L Ch R = 1 ,54774.9 ,516.4,530,543.6
XS GIS Cut Line= 4
     1902942.791      674122.933     1902647.652      674444.113
     1902513.103      674743.592     1902421.957      675273.106
#Sta/Elev= 30
       0  842.82    19.4   839.7    77.6  823.91   164.8  791.24   213.2  771.69
   300.5  724.37   416.8  680.96   455.5  673.28   532.8  670.47   561.7  662.58
     581   661.8   629.3   662.8   667.9  674.22     784  700.18   832.9  726.71
   891.5  770.17     911  778.81   930.6  784.17   950.1  780.05   979.4  766.99
  1028.3  731.37    1038  726.31  1086.9  715.03  1096.7  716.53  1106.4  722.44
    1126  738.72  1184.6  774.14  1262.7  818.16  1282.3  827.24  1301.8  833.51
#Mann= 3 , 0 , 0
       0     .07       0   561.7    .045       0   629.3      .1       0
Bank Sta=561.7,629.3
XS Rating Curve= 0 ,0
Exp/Cntr=0.3,0.1

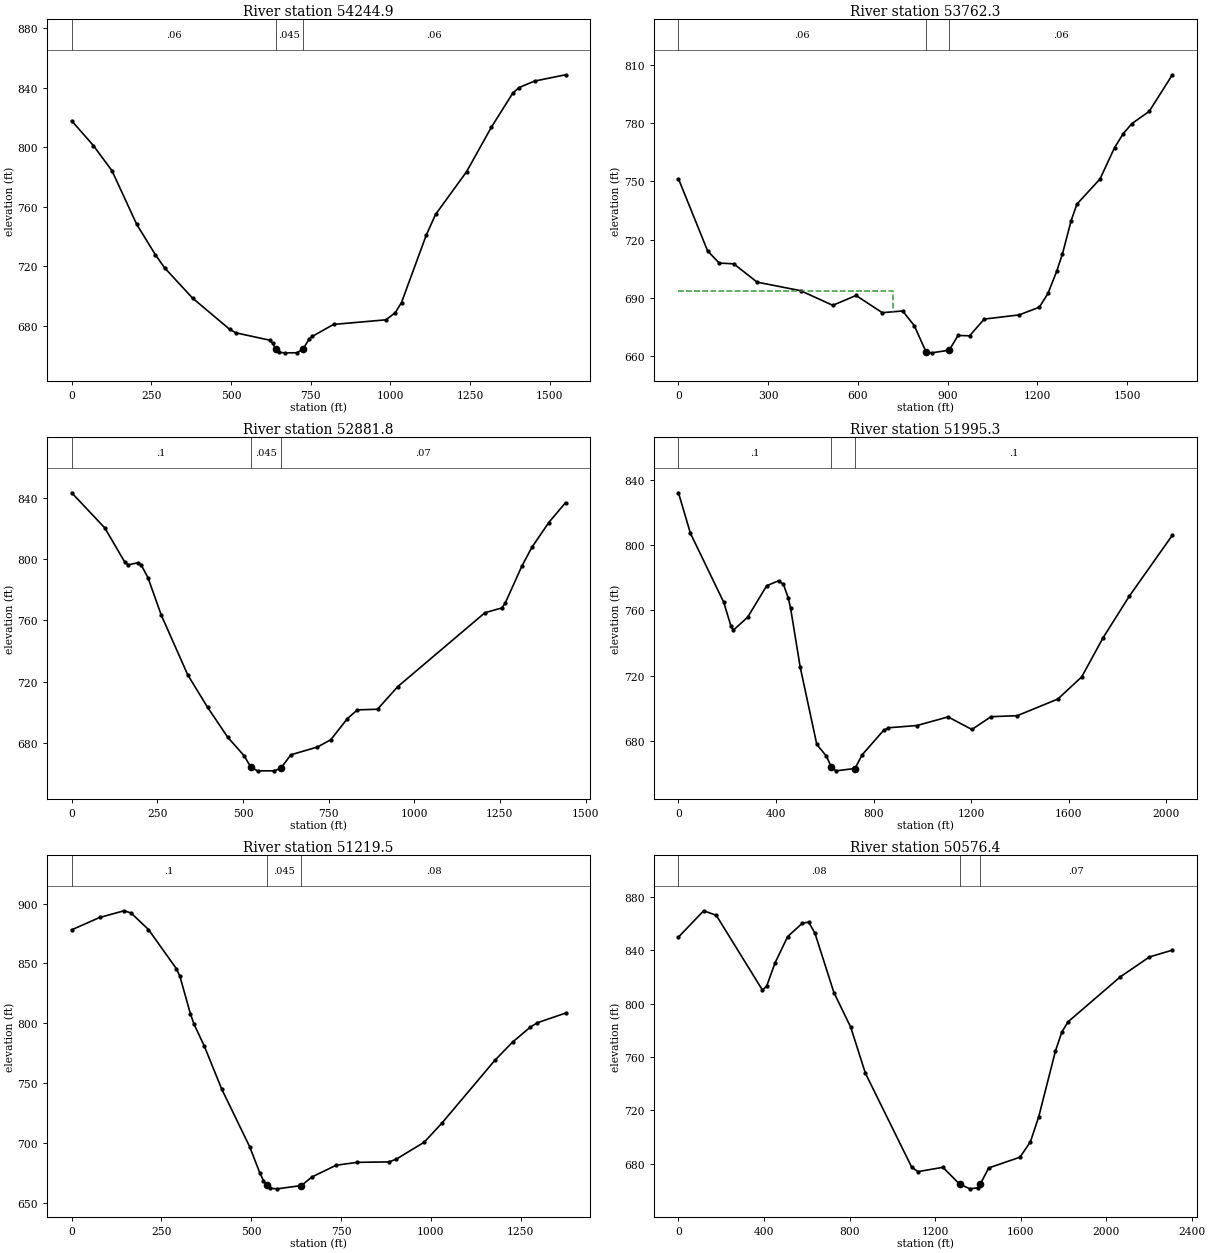
Type RM Length L Ch R = 1 ,54244.9 ,484.6,482.6,480.6
XS GIS Cut Line= 4
     1902751.818      673858.176     1902326.471      674166.335
     1902057.374      674331.266     1901510.499      674782.655
#Sta/Elev= 30
       0  817.64    68.1  801.01   126.4   784.1   204.3  747.96   262.6  727.66
   291.8   718.8   379.3  698.49   496.1  677.47   515.5  675.13   620.9  670.23
   630.4  668.18     640   664.2   649.6  662.03   668.7   661.7     707  661.74
   726.1  664.22   745.2  671.02   754.8  672.72   821.7  680.79   986.6   683.9
  1015.7  688.74  1035.1  695.52  1112.8   740.8    1142   754.7  1239.1  783.36
  1316.8  813.21  1384.8  836.35  1404.3     840  1452.8  844.33    1550  848.56
#Mann= 3 , 0 , 0
       0     .06       0     640    .045       0   726.1     .06       0
Bank Sta=640,726.1
XS Rating Curve= 0 ,0
Exp/Cntr=0.3,0.1

Type RM Length L Ch R = 1 ,53762.3 ,885.6,880.6,875.5
XS GIS Cut Line= 4
     1902560.846      673337.342     1901979.249      673810.433
     1901697.131      674018.766     1901276.124      674374.669
#Sta/Elev= 30
       0   751.3    97.4  714.21   136.3  707.91     185  707.52   262.9  698.11
   408.9  693.68     516  686.16   593.9  691.22   681.6  682.38   749.7  683.26
   788.7  675.69   827.6  662.27   847.1   661.7   905.6  663.07   934.8  670.63
   973.8  670.49  1022.5  679.08  1139.1  681.22  1206.8  685.19  1235.8  692.29
  1264.8  703.67  1284.2  712.68  1313.2  729.74  1332.5  738.26  1409.9  751.24
  1458.3  767.29  1487.3  774.51  1516.3  779.71  1574.3  786.01  1651.7  804.85
#Mann= 3 , 0 , 0
       0     .06       0   827.6    .045       0   905.6     .06       0
#XS Ineff= 2 , 0
          716.39  693.33
Permanent Ineff=
       F       F
Bank Sta=827.6,905.6
XS Rating Curve= 0 ,0
Exp/Cntr=0.3,0.1

Type RM Length L Ch R = 1 ,52881.8 ,905.5,886.5,867.5
XS GIS Cut Line= 4
     1901660.673      672813.905     1901400.256      673100.363
     1901108.589      673438.905     1900978.381      674032.655
#Sta/Elev= 30
       0  843.35    96.8  820.36   154.8  798.16   164.5  796.22   193.6  797.67
   203.2  796.04   222.6  787.96   261.3  763.58   338.8  724.42   396.8  703.18
   455.1   683.8   503.7  671.47   523.1  664.06   542.6   661.7   591.1  661.71
   610.6  663.37   639.7  672.17   717.4  677.27   756.3  682.01   804.8   695.8
     834  701.52   892.8  701.94   951.6  716.66  1206.6  765.02  1255.6   768.1
  1265.4  771.19  1314.4  795.55  1343.8  807.85  1392.8  823.93  1441.8  836.92
#Mann= 3 , 0 , 0
       0      .1       0   523.1    .045       0   610.6     .07       0
Bank Sta=523.1,610.6
XS Rating Curve= 0 ,0
Exp/Cntr=0.3,0.1

Type RM Length L Ch R = 1 ,51995.3 ,789.1,775.8,762.5
XS GIS Cut Line= 4
     1900499.214      672089.946     1900535.673      672626.405
     1900587.756      673053.488     1900728.381      674100.363
#Sta/Elev= 30
       0  831.98    48.9  807.22   185.8  764.83   215.1  750.37   224.8  747.84
   283.5  755.75   361.7  775.07   410.6   778.1   430.2  775.88   449.7  767.71
   459.5  761.36   498.6  725.47     567  677.86   606.1  670.74   625.7  664.24
   645.3   661.7   723.5  663.13   752.8  671.52   840.8   686.5   860.4  688.06
   977.7  689.46  1104.9  694.73  1202.7  687.03  1280.9  694.86  1388.5  695.47
  1554.8  705.66  1652.6  719.22  1740.6  743.29  1848.2  768.78  2024.2  805.98
#Mann= 3 , 0 , 0
       0      .1       0   625.7    .045       0   723.5      .1       0
Bank Sta=625.7,723.5
XS Rating Curve= 0 ,0
Exp/Cntr=0.3,0.1

Type RM Length L Ch R = 1 ,51219.5 ,642.4,643.1,643.7
XS GIS Cut Line= 4
     1899728.381      672928.488     1900056.506      673246.196
     1900259.631      673464.946     1900436.714      674058.696
#Sta/Elev= 30
       0  878.07    77.7  888.39   145.8  893.99   165.2  892.17   213.8  878.32
   291.5  845.61   301.2  839.28   330.4  808.04   340.1  799.61   369.3  780.86
   417.9  744.88   495.2  697.07   524.1  674.74   533.8  668.67   543.4  664.62
     553  662.17   572.3  661.71   639.7  664.48   668.6  671.59     736  681.41
   794.6  683.83   883.1  684.22   902.8  686.38   981.4  700.67  1030.6  716.64
  1178.2  769.16  1227.3   784.3  1276.5  796.76  1296.2  800.46  1374.8  808.53
#Mann= 3 , 0 , 0
       0      .1       0   543.4    .045       0   639.7     .08       0
Bank Sta=543.4,639.7
XS Rating Curve= 0 ,0
Exp/Cntr=0.3,0.1

Type RM Length L Ch R = 1 ,50576.4 ,432.4,426.9,421.4
XS GIS Cut Line= 4
     1899316.923      672678.488     1899732.374      673739.165
     1899971.089      674034.304     1900491.923      674628.922
#Sta/Elev= 30
       0  849.89   117.8   869.6   176.8  866.21   392.8  810.13   412.4  813.16
   451.7  830.59   510.6  850.26   579.4  860.32   608.8  861.08   638.3  852.72
   726.7  808.38   805.2  782.45     874  747.92    1090  677.69  1119.5  674.18
  1236.5  677.42  1314.3  664.84  1362.8   661.3  1401.9  662.13  1411.7     665
  1450.6  676.96  1596.8  685.01  1645.6  696.55  1684.6  715.42  1762.7  764.62
    1792  778.57  1821.3   786.4  2065.2  820.03  2201.8     835  2309.2  840.13
#Mann= 3 , 0 , 0
       0     .08       0  1314.3    .045       0  1411.7     .07       0
Bank Sta=1314.3,1411.7
XS Rating Curve= 0 ,0
Exp/Cntr=0.3,0.1

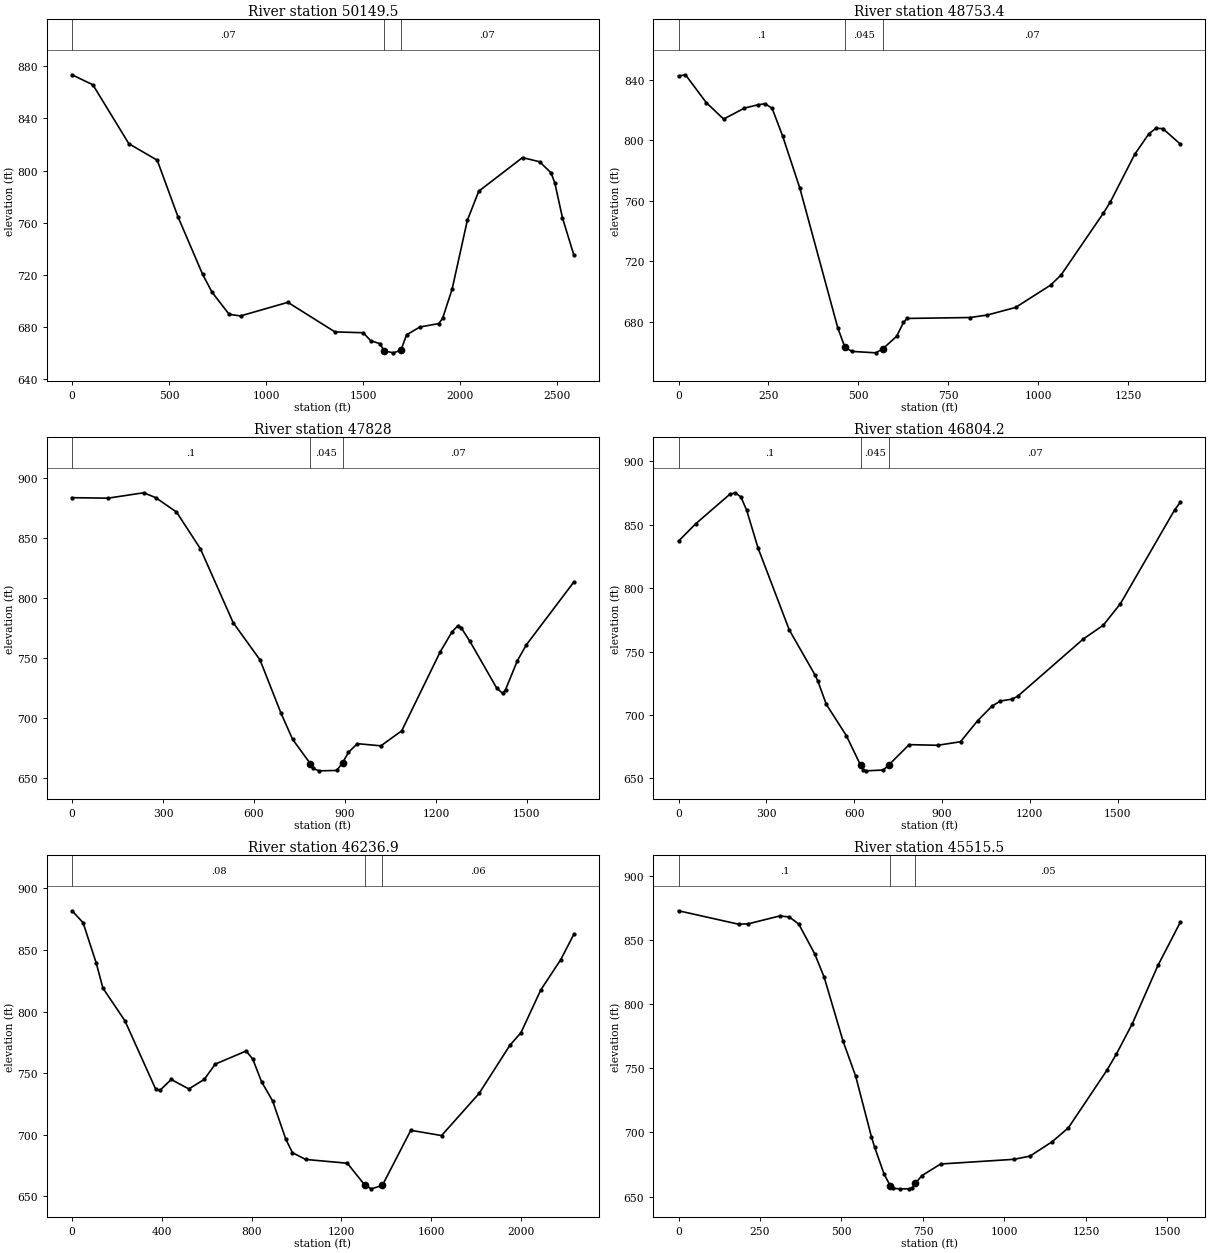
Type RM Length L Ch R = 1 ,50149.5 ,1396.5,1396.1,1395.7
XS GIS Cut Line= 4
     1898082.548       674017.03     1899191.923      673933.696
     1899733.589      674345.155     1900072.131      675063.905
#Sta/Elev= 30
       0  873.34   107.4  865.65   292.8  820.54   439.1  807.92   546.5  764.42
   673.4  720.41   722.2  706.72     810  689.89   868.5  688.66  1112.5  699.08
  1355.4  676.44  1501.2   675.8  1540.1  669.62  1588.7  667.38  1608.1  661.92
  1656.7   660.4  1695.6  662.44  1724.7  674.18  1792.7  680.15  1890.8   682.8
  1910.4  686.82  1959.5  709.16  2037.9  761.83  2096.8  784.18  2322.4  809.93
  2410.7  806.71  2469.5  798.29  2489.1  790.45  2528.4  763.81  2587.2  735.27
#Mann= 3 , 0 , 0
       0     .07       0  1608.1    .045       0  1695.6     .07       0
Bank Sta=1608.1,1695.6
XS Rating Curve= 0 ,0
Exp/Cntr=0.3,0.1

Type RM Length L Ch R = 1 ,48753.4 ,942.2,925.4,908.5
XS GIS Cut Line= 4
      1897944.18      674364.165     1898230.638      674542.117
     1898486.714      674728.749     1899090.013      675158.436
#Sta/Elev= 30
       0  842.34    19.3  843.12    77.1  824.74   125.3   813.9   183.1  821.11
   221.6  823.38   240.9  823.97   260.2  820.92   289.1   802.9   337.2  768.27
   442.8  675.98   462.1  663.52   481.3  660.59   548.5  659.63   567.7  662.26
   606.1  670.51   625.3  679.68   634.9  682.33     810  682.93   858.8  684.61
   936.7  689.57  1034.2  704.32  1063.4  711.03  1180.4  751.66  1199.9  759.02
  1268.1  790.66  1307.1  804.08  1326.6  807.74    1346  807.63  1394.8  797.37
#Mann= 3 , 0 , 0
       0      .1       0   462.1    .045       0   567.7     .07       0
Bank Sta=462.1,567.7
XS Rating Curve= 0 ,0
Exp/Cntr=0.3,0.1

Type RM Length L Ch R = 1 ,47828   ,1021.3,1023.8,1022.7
XS GIS Cut Line= 4
     1897553.555      675605.485     1898221.957      675575.103
      1898569.18       675536.04      1899198.52      675631.526
#Sta/Elev= 30
       0  883.22   118.1  882.82   236.2   887.3   275.5   883.3   344.4  871.29
   423.1   840.8   531.3  779.28   619.9  748.27   688.5  704.31   727.3  682.26
   785.6  662.05   795.3  658.03   814.7     656   872.9  656.31   892.3  662.83
   911.7  671.42   940.9   678.6  1018.5   676.8  1087.1  689.25  1214.4  755.09
  1253.5  771.72  1273.1  776.84  1282.9  775.23  1312.3  763.66  1400.4  724.91
    1420  720.44  1429.8  723.64    1469  747.78  1498.4  760.84    1655   813.1
#Mann= 3 , 0 , 0
       0      .1       0   785.6    .045       0   892.3     .07       0
Bank Sta=785.6,892.3
XS Rating Curve= 0 ,0
Exp/Cntr=0.3,0.1

Type RM Length L Ch R = 1 ,46804.2 ,578.9,567.3,555.3
XS GIS Cut Line= 4
     1897727.166      676612.429     1898182.895      676595.068
     1898669.006      676556.006     1899432.895      676456.179
#Sta/Elev= 30
       0  837.05    58.2  850.64   174.7  873.89   194.1  875.16   213.5  871.73
   232.9  861.26   271.7  831.56   378.4  767.02   465.8  731.73   475.6  726.96
   504.8   708.4   573.1  683.81   621.9   660.4   631.6  656.76   641.4     656
   699.9  656.65   719.4   660.9   787.7  676.65   885.2  676.14   963.2  678.93
  1021.8  695.53  1070.5  706.97  1099.8  711.04  1138.8  712.49  1158.3  714.73
  1382.6  759.89  1450.8  770.76  1509.3  787.71  1694.6  861.64  1714.1  867.68
#Mann= 3 , 0 , 0
       0      .1       0   621.9    .045       0   719.4     .07       0
Bank Sta=621.9,719.4
XS Rating Curve= 0 ,0
Exp/Cntr=0.3,0.1

Type RM Length L Ch R = 1 ,46236.9 ,741.8,721.5,701.2
XS GIS Cut Line= 4
       1897644.7      677858.089     1898512.756      677150.624
      1898890.36      676890.207     1899432.895      676516.943
#Sta/Elev= 30
       0  881.88    49.1  872.21     108  839.24   137.5  819.09   235.8  792.46
   373.3  736.76   392.9   736.2     442  744.84   520.6  737.15   589.4  744.92
   638.5  757.33     776  767.96   805.5  761.44   844.8  742.99   893.9   727.5
   952.8  696.39   982.3  685.41  1041.2  679.89  1227.2   676.8  1305.3  658.97
  1334.5     656  1383.3  658.77  1510.2  703.57  1647.3  699.27  1814.4  733.45
    1952  772.64  2001.2  782.81  2089.6  817.58  2178.1  842.02  2237.1  862.83
#Mann= 3 , 0 , 0
       0     .08       0  1305.3    .045       0  1383.3     .06       0
Bank Sta=1305.3,1383.3
XS Rating Curve= 0 ,0
Exp/Cntr=0.3,0.1

Type RM Length L Ch R = 1 ,45515.5 ,488.3,486.7,485.2
XS GIS Cut Line= 4
     1899280.985      678057.742     1899289.666      677523.887
     1899311.367      677215.728     1899476.298      676538.644
#Sta/Elev= 30
       0  872.55   184.4  862.09   213.6  862.38   310.6  868.52   339.8  867.75
   368.9  862.17   417.4  839.24   446.6  821.03   504.8  771.03   543.6  743.73
   591.8   696.6   601.5  688.62   630.5  667.63   649.8   658.3   659.4  656.38
   678.7     656   707.7     656   717.4  656.92     727  660.23   746.3  666.25
   804.2  675.34  1029.3  678.99  1078.4  681.48  1147.1  692.81  1196.2  703.53
    1314   748.2  1343.4  760.92  1392.5  784.67    1471  829.97  1539.7  863.66
#Mann= 3 , 0 , 0
       0      .1       0   649.8    .045       0     727     .05       0
Bank Sta=649.8,727
XS Rating Curve= 0 ,0
Exp/Cntr=0.3,0.1

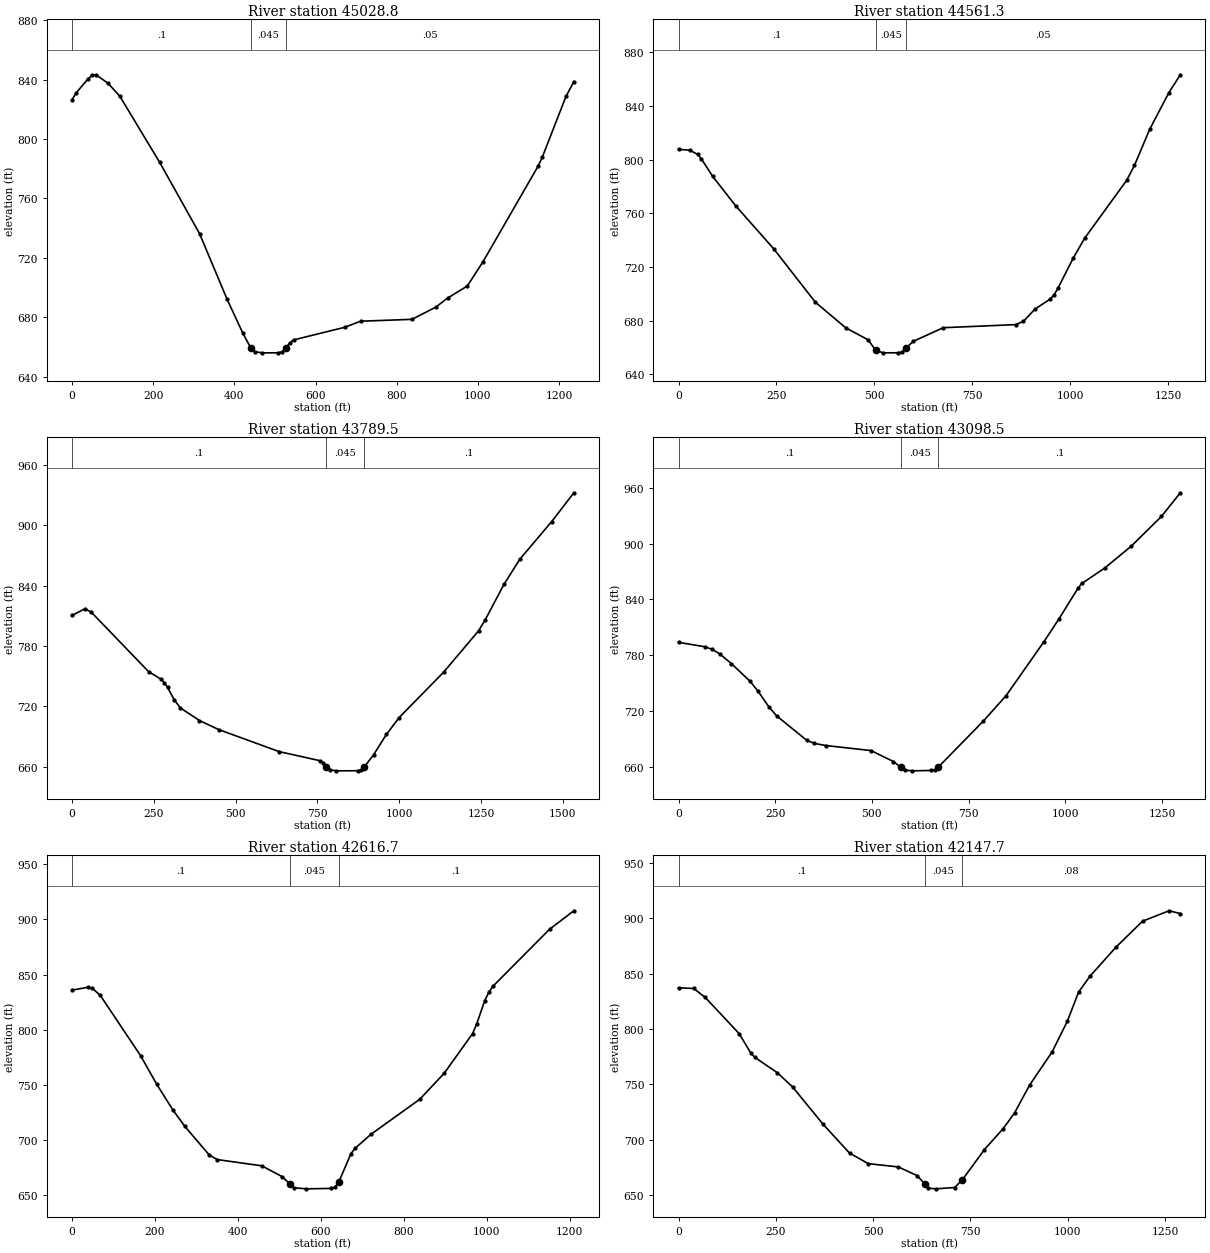
Type RM Length L Ch R = 1 ,45028.8 ,473.3,467.5,461.6
XS GIS Cut Line= 4
     1899836.541      677810.346     1899784.457      677480.485
     1899784.457      677220.068     1899780.117      676577.707
#Sta/Elev= 30
       0  826.49     9.8  831.06    39.3  840.52    49.1  842.89    58.9  843.33
    88.4  837.69   117.9  828.78   216.1  784.24   314.3  736.24   382.2  692.01
   420.8  669.29     440  659.49   449.7  656.78     469     656   507.6  656.02
   517.2  656.64   526.8  659.23   536.5  662.73   546.1  664.72   672.2  673.23
   711.2  677.31   837.7  678.56   896.1  686.73   925.3  692.83     974  701.01
  1012.9  717.42  1149.1  782.03  1158.9  787.82  1217.3  828.75  1236.7  838.76
#Mann= 3 , 0 , 0
       0      .1       0     440    .045       0   526.8     .05       0
Bank Sta=440,526.8
XS Rating Curve= 0 ,0
Exp/Cntr=0.3,0.1

Type RM Length L Ch R = 1 ,44561.3 ,753,771.8,790.6
XS GIS Cut Line= 4
     1900396.436       677714.86     1900270.568      677337.256
     1900196.784      677059.478     1900088.277       676473.54
#Sta/Elev= 30
       0  807.55    29.1  806.94    48.5  803.79    58.2  800.49    87.4  787.36
   145.6   765.6   242.7  733.61   349.5  693.67   426.8  674.67   484.2  665.69
   503.4  657.84   522.6     656   560.9  656.05   570.5  656.68   580.1  659.35
   599.2  664.55   675.9  674.71   861.3  677.02   880.8  679.48   910.1  688.59
   949.2  696.08     959  699.23   968.7  704.08  1007.8  726.54  1037.1  741.42
  1144.6  784.63  1164.1  795.58  1203.2  822.56    1252  849.76  1281.3  863.11
#Mann= 3 , 0 , 0
       0      .1       0   503.4    .045       0   580.1     .05       0
Bank Sta=503.4,580.1
XS Rating Curve= 0 ,0
Exp/Cntr=0.3,0.1

Type RM Length L Ch R = 1 ,43789.5 ,676.1,691,705.5
XS GIS Cut Line= 4
     1900583.068      677727.881     1900873.867      677133.262
     1901038.798      676872.846     1901273.173      676360.693
#Sta/Elev= 30
       0  810.45    38.9  816.97    58.4  813.76   233.6  754.64   272.6  746.86
   282.3  743.55     292   738.8   311.5  726.87     331   718.5   389.4  705.98
   447.8  697.03   632.7  675.12   758.2  666.03   767.9  663.98   777.5  659.95
   787.1  657.33   806.4     656   873.8   656.1   883.5  657.04   893.1  659.89
     922  672.23   960.5  692.15   999.3  708.86  1135.2  753.96  1242.1  795.07
  1261.5  805.47  1319.8  841.22  1368.3  866.27  1465.4  903.55  1533.4  932.26
#Mann= 3 , 0 , 0
       0      .1       0   777.5    .045       0   893.1      .1       0
Bank Sta=777.5,893.1
XS Rating Curve= 0 ,0
Exp/Cntr=0.3,0.1

Type RM Length L Ch R = 1 ,43098.5 ,477.7,481.8,485.8
XS GIS Cut Line= 4
     1900734.978      677779.964     1901164.666      677619.374
     1901490.186      677493.506     1901967.617      677384.999
#Sta/Elev= 30
       0  793.95    68.3  789.18    87.8  786.28   107.4  781.26   136.6  771.12
   185.4  751.93     205  741.76   234.2  724.32   253.8  714.87   331.8  688.63
   351.4  685.35   380.6  683.12   497.5  677.69   555.7  665.88     575  659.61
   584.8  656.78   604.1  655.92   652.6  656.34   662.3  657.29     672   660.1
   788.3  709.49   846.9   736.7   944.8  794.68     984  819.44  1032.9  852.16
  1042.7  857.19  1101.5  873.62    1170  897.09  1248.4  929.12  1297.3  954.58
#Mann= 3 , 0 , 0
       0      .1       0     575    .045       0     672      .1       0
Bank Sta=575,672
XS Rating Curve= 0 ,0
Exp/Cntr=0.3,0.1

Type RM Length L Ch R = 1 ,42616.7 ,450.7,469,487.3
XS GIS Cut Line= 4
     1900891.228      678144.547     1901251.471      678062.082
     1901568.311      678001.318     1902084.805      677957.915
#Sta/Elev= 30
       0  836.01    38.9   838.6    48.6  837.71    68.1  831.23   165.3  776.57
   204.2  750.71   243.1  727.42   272.3   712.4   330.7  686.68   350.1  682.43
   457.6  676.78   506.4  667.04     526  660.17   535.8  656.86   565.1   655.9
   623.7  656.28   633.5  657.19   643.3  661.87   672.6   687.7   682.4  692.53
   721.5  705.45   838.9  737.11   897.6   760.6     966  796.52   975.8  805.03
   995.3  826.25  1005.1  833.91  1014.9  839.35  1151.8  891.13  1210.5   907.9
#Mann= 3 , 0 , 0
       0      .1       0     526    .045       0   643.3      .1       0
Bank Sta=526,643.3
XS Rating Curve= 0 ,0
Exp/Cntr=0.3,0.1

Type RM Length L Ch R = 1 ,42147.7 ,674.7,695.5,716.3
XS GIS Cut Line= 4
     1900834.805      678200.971     1901247.131      678352.881
     1901585.673      678591.596     1901928.555      678860.693
#Sta/Elev= 30
       0  837.13    39.1  836.51    68.4  828.51   156.2  795.67   185.5  778.43
   195.3  774.59   253.9  760.59     293  747.83   371.1  714.28   439.4  688.16
   487.6  678.64   564.7  675.68   612.8  667.91   632.1  660.69   641.7  656.58
     661  655.93   709.2  657.12   728.4  663.65   786.2  691.36   834.4  710.31
   863.4   724.3   902.1  749.35   960.2  779.46     999  806.89    1028  833.21
  1057.1  847.49  1124.9  874.06  1192.7  897.23  1260.5  906.56  1289.5  904.07
#Mann= 3 , 0 , 0
       0      .1       0   632.1    .045       0   728.4     .08       0
Bank Sta=632.1,728.4
XS Rating Curve= 0 ,0
Exp/Cntr=0.3,0.1