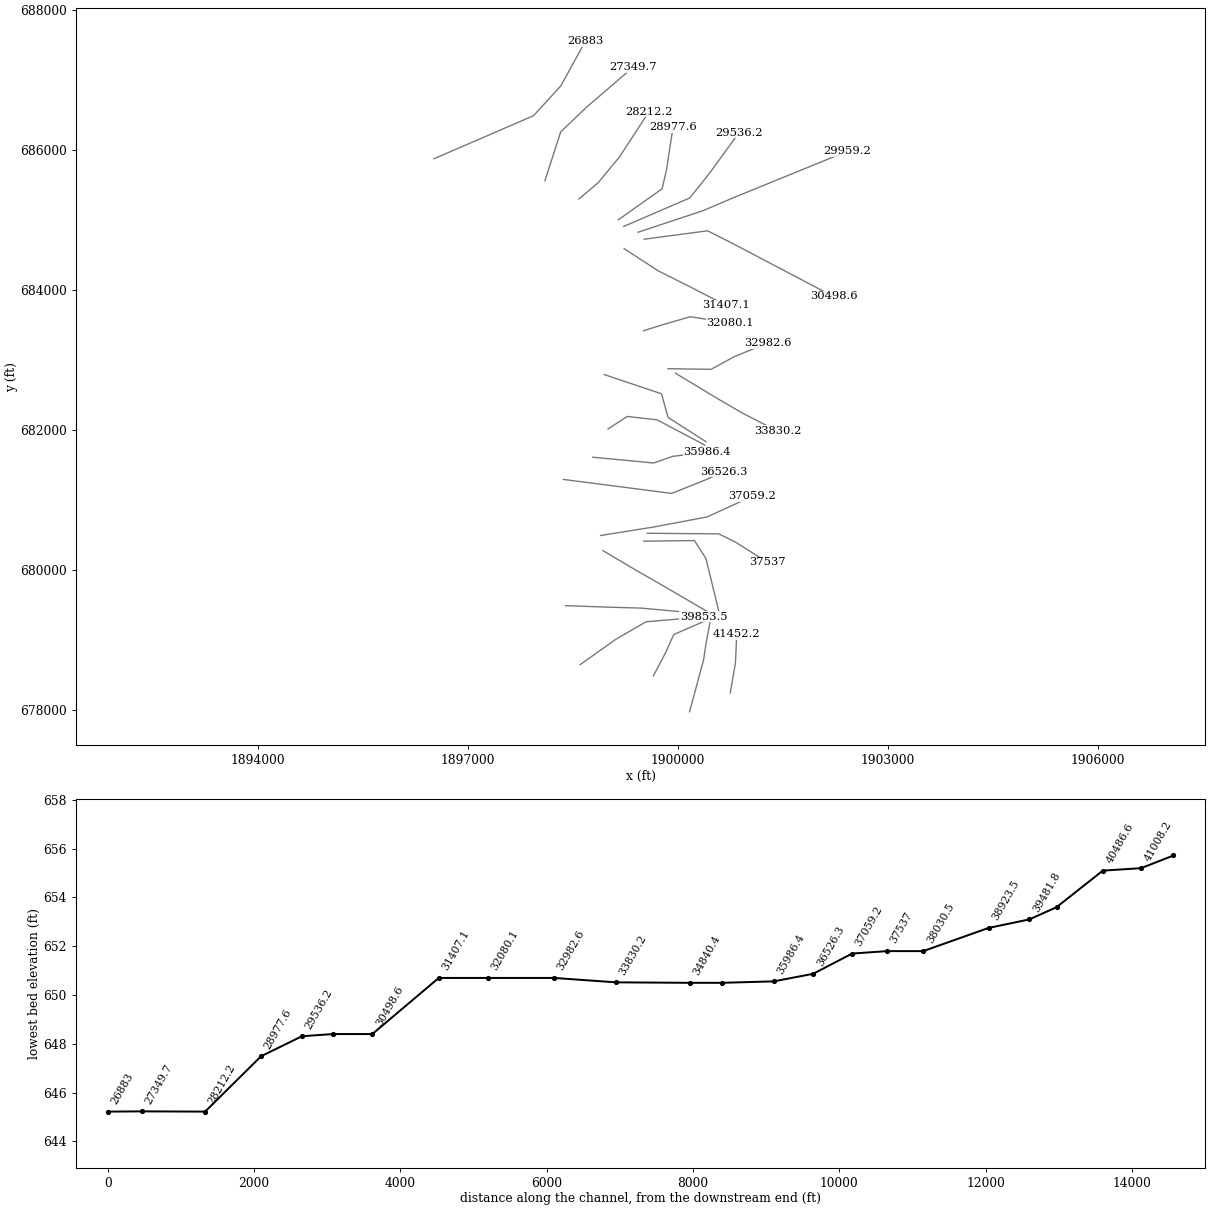
HEC-RAS study LtlKwhaRvr.prj: LtlKwhaRvr

--- LtlKwhaRvr.g01 (geometry) --- (continued)

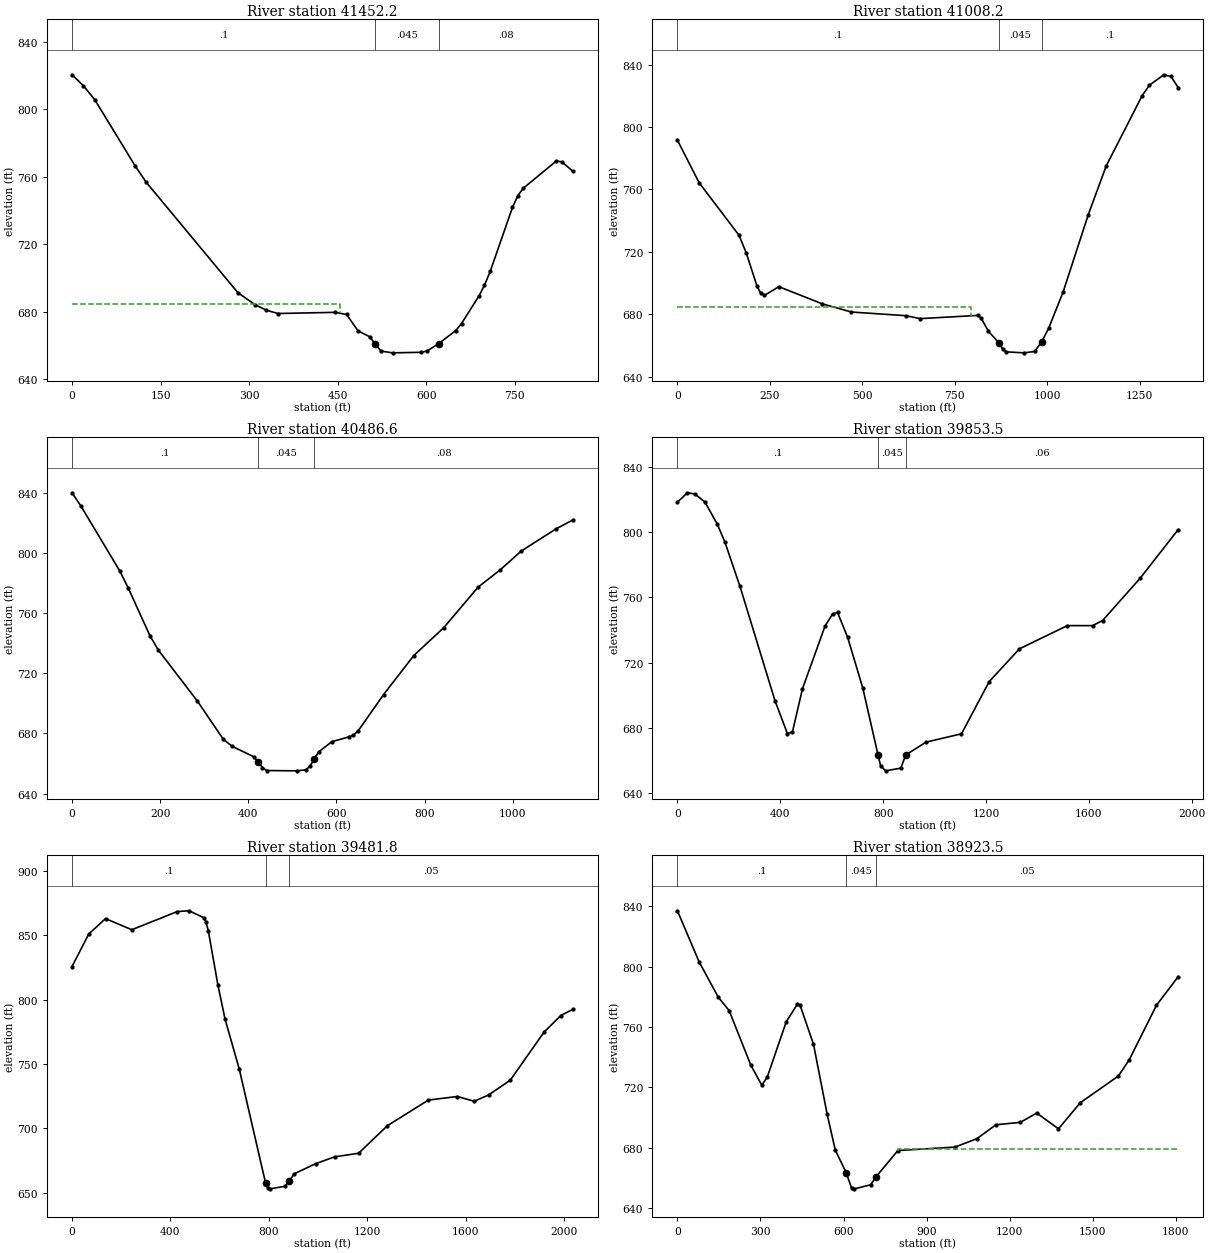
Type RM Length L Ch R = 1 ,41452.2 ,446.5,443.9,441.4
XS GIS Cut Line= 4
     1900747.999      678248.714     1900821.784      678678.401
     1900834.805      678960.519     1900834.805      679090.728
#Sta/Elev= 30
       0  820.44    19.4  813.92    38.8  805.56   106.6  766.65     126  756.64
     281  691.38     310  684.26   329.4  680.97   348.8  679.02   445.7  679.71
   465.2  678.45   484.7  668.72   504.2   665.3   513.9  660.95   523.6  656.76
   543.1  655.72   591.8  656.03   601.5  656.82     621  661.08   650.2  668.93
     660   673.1   689.2  689.21   698.9  695.74   708.7  704.08   746.3  741.86
   755.6   748.9   764.9  753.29   820.7  769.38     830  768.82   848.6  763.31
#Mann= 3 , 0 , 0
       0      .1       0   513.9    .045       0     621     .08       0
#XS Ineff= 2 , 0
          454.85  684.61
Permanent Ineff=
       F       F
Bank Sta=513.9,621
XS Rating Curve= 0 ,0
Exp/Cntr=0.3,0.1

Type RM Length L Ch R = 1 ,41008.2 ,528.1,521.7,515.3
XS GIS Cut Line= 4
     1900166.402      677979.617     1900366.055      678717.464
     1900405.117       678973.54     1900465.881      679299.061
#Sta/Elev= 30
       0   791.6    58.8  764.28   166.6  730.63   186.2  719.25   215.6   697.8
   225.4  693.47   235.2     692   274.4  697.63     392  686.61   470.4  681.39
   617.4  679.04   656.6  677.15   812.4   679.2     822  677.33   841.1  669.04
   869.9  661.55   879.5  657.78   889.1  655.83   937.1   655.2   965.9  656.06
     985   662.1  1004.2  671.01  1042.9  693.99  1111.1  743.66  1159.8  775.07
  1257.2  820.23  1276.6  826.86  1315.6  833.55  1335.1  832.45  1354.6  825.28
#Mann= 3 , 0 , 0
       0      .1       0   869.9    .045       0     985      .1       0
#XS Ineff= 2 , 0
          793.65  684.31
Permanent Ineff=
       F       F
Bank Sta=869.9,985
XS Rating Curve= 0 ,0
Exp/Cntr=0.3,0.1

Type RM Length L Ch R = 1 ,40486.6 ,647.2,633,618.3
XS GIS Cut Line= 4
     1899649.909      678491.769      1899819.18       678812.95
     1899940.707      679082.047     1900379.075      679273.019
#Sta/Elev= 30
       0  839.93    19.6  831.37   107.9   788.2   127.6  776.62   176.6  745.06
   196.2  735.22   284.6  701.45   343.4  676.02   363.1  671.47   412.3  664.46
   422.1  661.26     432  657.28   441.8   655.3   510.7   655.1   530.4  655.75
   540.2  658.18   550.1  663.25   559.9  667.68   589.4  674.46   628.8  677.72
   638.6  678.93   648.5  681.32   707.1  705.82   775.4  731.67   843.7  750.32
   921.8  777.28   970.6  788.43  1019.4  801.19  1097.4  815.76  1136.5  821.86
#Mann= 3 , 0 , 0
       0      .1       0   422.1    .045       0   550.1     .08       0
Bank Sta=422.1,550.1
XS Rating Curve= 0 ,0
Exp/Cntr=0.3,0.1

Type RM Length L Ch R = 1 ,39853.5 ,384.1,371.7,359.3
XS GIS Cut Line= 4
     1898603.902       678652.36     1899111.714      679012.603
     1899545.742      679264.339     1900366.055      679333.783
#Sta/Elev= 30
       0  818.48    38.9  824.25    68.1  823.51     107  818.58   155.6  804.86
   184.8  793.93   243.2  766.86   379.4  696.67     428  676.35   447.5  677.61
   486.4  704.01     574   742.4   603.2  749.82   622.6  750.84     662  735.53
     721  704.38     780  663.48   789.9  656.81   809.5   653.6   868.6  655.26
   888.2  663.38     967  671.23  1104.7  676.33  1212.6  708.39  1330.2  728.49
  1516.4  742.73  1614.4  742.71  1653.6  745.85  1800.6  772.01  1947.6  801.68
#Mann= 3 , 0 , 0
       0      .1       0     780    .045       0   888.2     .06       0
#XS Ineff= 2 , 0
          615.38  750.29
Permanent Ineff=
       F       F
Bank Sta=780,888.2
XS Rating Curve= 0 ,0
Exp/Cntr=0.3,0.1

Type RM Length L Ch R = 1 ,39481.8 ,569.2,558.3,547.3
XS GIS Cut Line= 4
     1898395.568      679494.374     1899007.548      679472.672
     1899471.957      679459.651     1900426.818      679372.846
#Sta/Elev= 30
       0  825.77      68  851.03   136.1  863.01     243  854.38   427.7   868.5
   476.3  869.11   534.6  863.79   544.3  860.45     554   853.6   592.9  811.59
     622     785   680.1  745.95   786.6  657.76   796.3  653.86   805.9   653.1
     864  655.04   883.4  659.08   902.7  664.75   989.8   672.6  1067.3  677.95
    1165  680.75  1282.4  702.22  1448.7  722.06  1566.1  724.83  1634.6  721.14
  1693.3  726.01  1781.4  737.48  1918.4  774.75  1986.8  787.75  2035.8  792.53
#Mann= 3 , 0 , 0
       0      .1       0   786.6    .045       0   883.4     .05       0
Bank Sta=786.6,883.4
XS Rating Curve= 0 ,0
Exp/Cntr=0.3,0.1

Type RM Length L Ch R = 1 ,38923.5 ,903.5,893,882.5
XS GIS Cut Line= 4
     1898929.423      680279.964     1899419.874      679989.165
     1899701.992      679828.575     1900491.923      679368.506
#Sta/Elev= 30
       0  837.13    78.6  803.19   147.5  779.87   186.8  770.95   265.4  734.65
   304.8  721.47   324.4  726.79   393.2  763.56   432.6  775.01   442.4  774.82
   491.5  748.66   540.7  702.39   570.2  678.44   609.5   663.5   629.2   653.2
     639  652.75   698.1  655.44   717.7  660.79   796.4  678.15  1002.9  680.45
  1081.6     686  1150.4  695.24  1238.8  696.84  1297.8     703  1376.4  692.54
  1455.1  709.84  1592.7  727.56    1632  738.35  1730.3  774.44  1808.9  793.48
#Mann= 3 , 0 , 0
       0      .1       0   609.5    .045       0   717.7     .05       0
#XS Ineff= 2 , 0
                          796.61          679.42
Permanent Ineff=
       F       F
Bank Sta=609.5,717.7
XS Rating Curve= 0 ,0
Exp/Cntr=0.3,0.1

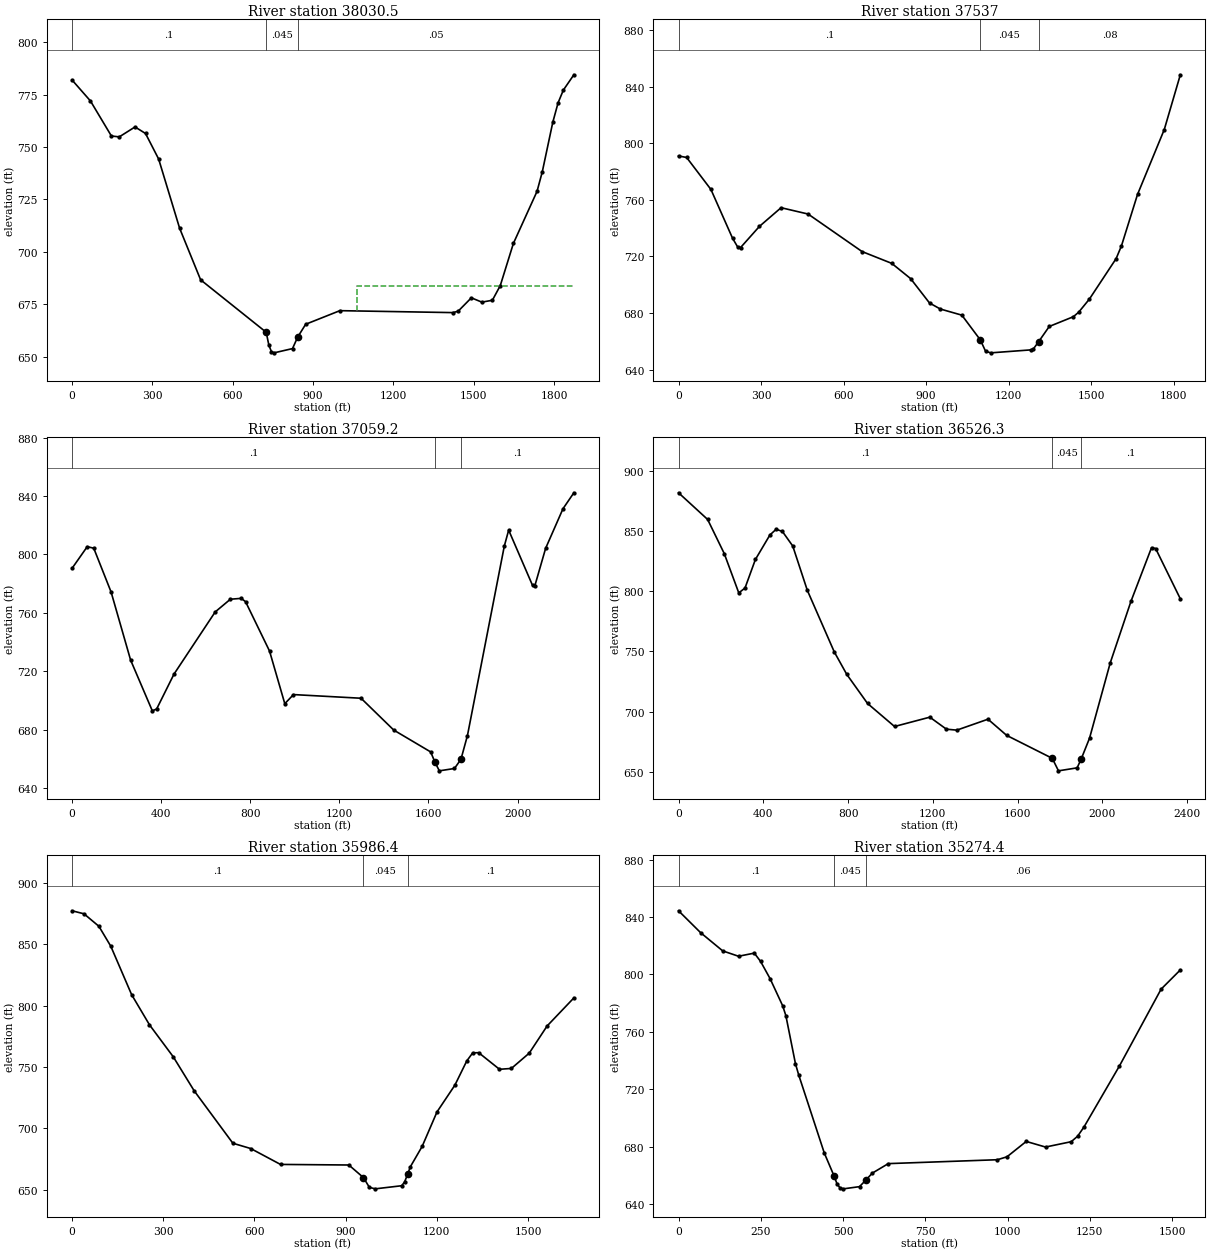
Type RM Length L Ch R = 1 ,38030.5 ,481.4,493.5,505.6
XS GIS Cut Line= 4
      1899511.02      680414.512     1900235.846      680423.193
     1900400.777      680167.117      1900600.43      679346.804
#Sta/Elev= 30
       0  782.01    68.6  772.02   146.9  755.28   176.3  754.88   235.1  759.61
   274.3  756.49   323.3  744.29   401.6  711.27     480  686.65   724.9  661.62
   734.7  655.55   744.5  652.31   754.4   651.8   823.1  653.83   842.8   659.4
   872.3  665.44    1000  671.93  1422.2     671  1441.8  671.69  1490.9  678.06
  1530.1     676  1569.4  676.89  1598.9  683.88  1647.9  704.02  1736.3   728.9
  1755.9  738.25  1795.2  761.94  1814.8  771.13  1834.5  777.21  1873.7  784.51
#Mann= 3 , 0 , 0
       0      .1       0   724.9    .045       0   842.8     .05       0
#XS Ineff= 2 , 0
                         1063.55          683.53
Permanent Ineff=
       F       F
Bank Sta=724.9,842.8
XS Rating Curve= 0 ,0
Exp/Cntr=0.3,0.1

Type RM Length L Ch R = 1 ,37537   ,458.3,477.9,497.6
XS GIS Cut Line= 4
     1899563.103       680527.36     1900583.068      680518.679
     1900824.388        680399.9     1901275.777      680113.442
#Sta/Elev= 30
       0  791.08    29.4  790.02   117.7  767.39   196.2  732.92   215.8  726.38
   225.6  726.32   294.2   741.3   372.7  754.48   470.8     750   666.9  723.46
   774.8   715.1   843.5   704.3   912.1  687.06   951.4   682.8  1029.6  678.46
  1096.8  660.94  1116.1   652.8  1135.3   651.8  1279.4  653.88    1289   654.4
  1308.4  659.62  1347.3  670.46  1434.8  677.35  1454.2  680.55  1493.1  689.81
  1590.3  718.47  1609.7   727.5  1668.1  763.89  1765.3   809.8  1823.6  848.52
#Mann= 3 , 0 , 0
       0      .1       0  1096.8    .045       0  1308.4     .08       0
Bank Sta=1096.8,1308.4
XS Rating Curve= 0 ,0
Exp/Cntr=0.3,0.1

Type RM Length L Ch R = 1 ,37059.2 ,534.7,532.8,530.2
XS GIS Cut Line= 5
     1898897.305      680495.386     1899656.853      680616.914
     1900416.402      680760.143     1900690.246      680885.119
     1901063.103      681055.282
#Sta/Elev= 30
       0   790.5    68.2  805.35    97.4  804.25   175.3  774.22   262.9  727.59
   360.3  692.83   379.7  694.08   457.6  717.98   642.6   760.6   710.8  769.31
   759.5   769.9     779  767.62   886.6   733.8   955.1  697.73   994.2  703.96
  1297.5  701.45  1444.3  679.64  1610.1  664.66  1629.5  657.57    1649   651.7
  1716.9  653.31  1746.1  659.63  1775.2  675.88  1940.7  805.71  1960.3  816.66
  2067.6  778.73  2077.4  778.29  2126.2  804.18  2204.2  831.33    2253  842.26
#Mann= 3 , 0 , 0
       0      .1       0  1629.5    .045       0  1746.1      .1       0
Bank Sta=1629.5,1746.1
XS Rating Curve= 0 ,0
Exp/Cntr=0.3,0.1

Type RM Length L Ch R = 1 ,36526.3 ,540.2,539.9,540
XS GIS Cut Line= 4
     1898365.186      681295.589     1899910.325      681095.936
     1900400.777      681291.249     1900656.853      681408.436
#Sta/Elev= 30
       0  881.63   137.2  859.51   215.6  831.21   284.2  798.57   313.6  802.56
   362.6  826.26   431.1  846.61   460.5  851.34   489.9  849.56   538.9  837.45
   607.5  800.73   734.9  749.52   793.7  730.93   891.7  706.79  1019.1  687.67
  1185.6  695.41    1264  685.43    1313  684.65    1460  693.72  1548.2  680.29
  1763.3  661.26  1792.6  650.87  1880.6  653.35  1900.2  660.85  1939.2  677.99
    2037  740.56  2134.4  791.44  2231.6  836.07    2251  835.38  2367.5  793.63
#Mann= 3 , 0 , 0
       0      .1       0  1763.3    .045       0  1900.2      .1       0
Bank Sta=1763.3,1900.2
XS Rating Curve= 0 ,0
Exp/Cntr=0.3,0.1

Type RM Length L Ch R = 1 ,35986.4 ,721.6,712,702.4
XS GIS Cut Line= 4
     1898786.193      681612.429     1899654.249      681529.964
     1899927.686       681625.45     1900413.798      681681.874
#Sta/Elev= 30
       0  877.33    39.2  874.86    88.2   864.7   127.4  848.43     196   808.9
   254.7  784.33   333.1  758.18   401.7  730.53   529.1  687.74   587.8  683.43
   685.8  670.47   910.6     670   958.8  659.73   978.2  651.76   997.5  650.56
  1084.4  653.09    1094  656.11  1103.7  662.28  1113.3  668.66  1151.9   685.2
  1200.7  713.29  1259.5  735.09  1298.6  754.84  1318.2  761.47  1337.8   761.6
  1406.3  748.06  1445.4  748.74  1504.2  761.23  1562.9  783.36    1651  806.26
#Mann= 3 , 0 , 0
       0      .1       0   958.8    .045       0  1103.7      .1       0
Bank Sta=958.8,1103.7
XS Rating Curve= 0 ,0
Exp/Cntr=0.3,0.1

Type RM Length L Ch R = 1 ,35274.4 ,461,434,407
XS GIS Cut Line= 4
     1899003.207      682016.075     1899276.645      682194.026
     1899701.992      682146.283     1900383.416       681786.04
#Sta/Elev= 30
       0  844.31    67.2  829.03   134.3  816.35   182.3  812.61   230.3   814.8
   249.5  808.96   278.3  796.97   316.6  778.04   326.2  771.23   355.4  737.66
   365.2  729.89     443  675.46   472.2  659.73   481.9  653.86   491.6  650.94
   501.3   650.5     550  652.03   569.4  656.63   588.9  661.45   637.5  668.08
   968.9  670.79   998.2  672.83  1056.7  683.54  1115.3  679.63  1193.3  683.35
  1212.8  687.15  1232.4  693.68  1339.7  736.04  1466.5  789.66    1525  803.08
#Mann= 3 , 0 , 0
       0      .1       0   472.2    .045       0   569.4     .06       0
Bank Sta=472.2,569.4
XS Rating Curve= 0 ,0
Exp/Cntr=0.3,0.1

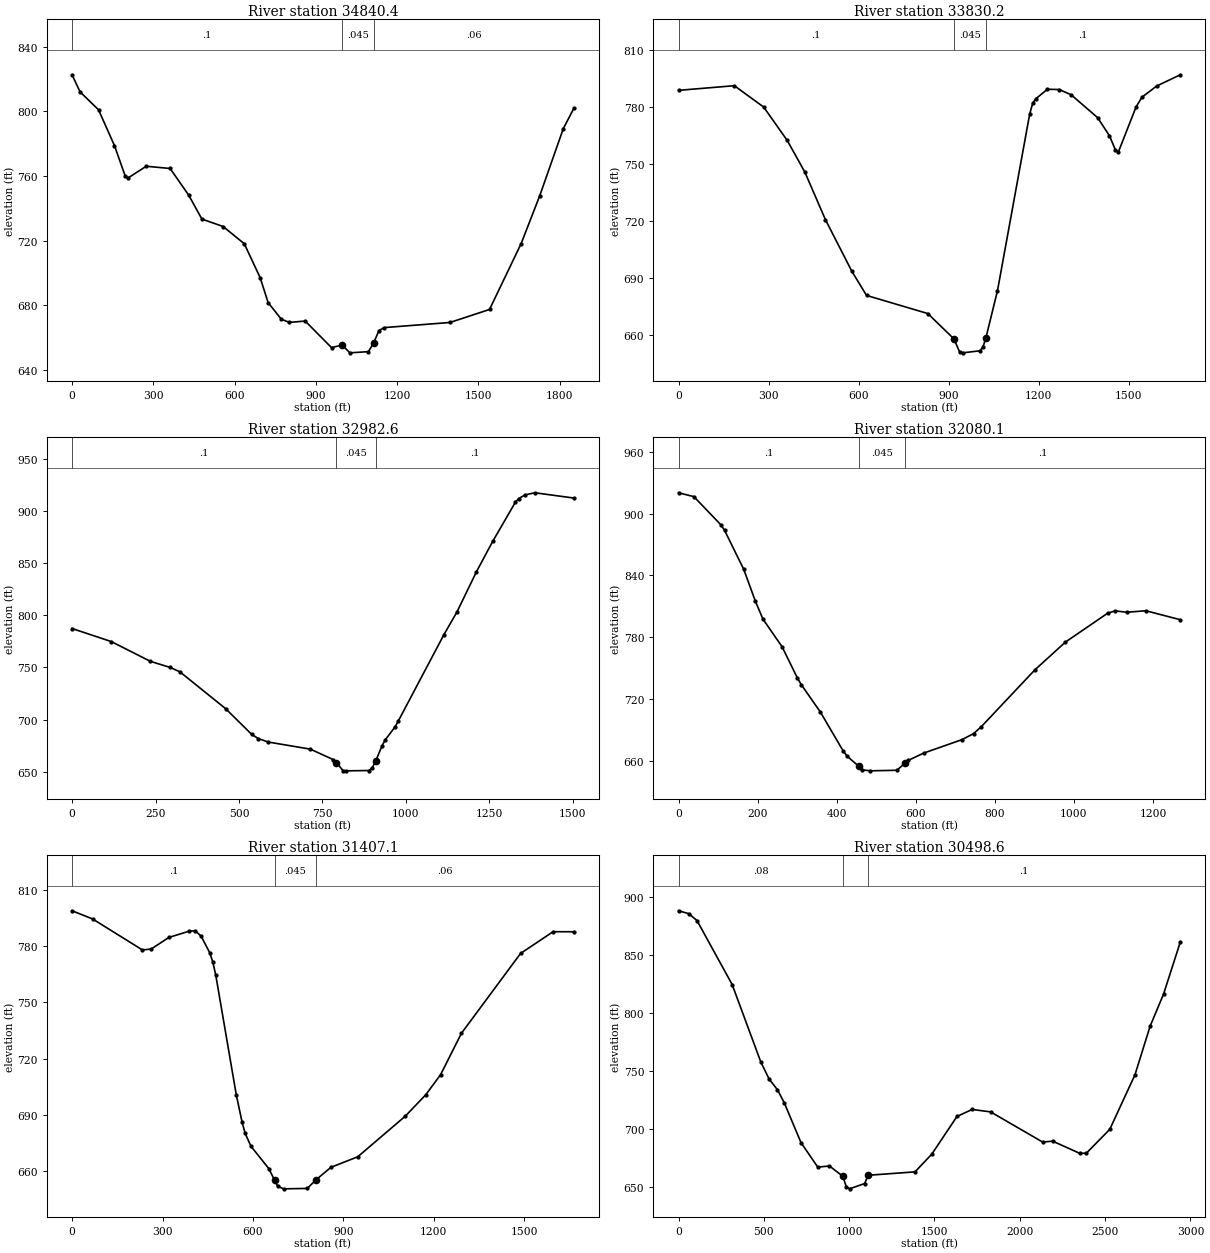
Type RM Length L Ch R = 1 ,34840.4 ,992.1,1010.2,1028.2
XS GIS Cut Line= 4
     1898950.256      682791.393     1899766.228      682517.088
     1899859.978      682180.282     1900400.777      681833.783
#Sta/Elev= 30
       0  822.64    29.4  812.06    97.8  800.95   156.5  778.79   195.6  760.27
   205.4  758.62   273.9  766.01     362  764.63   430.4  748.18   479.3  733.32
   557.6  728.71   635.8  718.06   694.6  696.98   723.9  681.59   772.8  671.29
   802.2  669.36   860.8  670.17     958  653.72   996.8  655.34  1025.9   650.5
  1093.9  651.23  1113.3  656.47  1132.8  664.26  1152.2  666.12  1395.4   669.3
  1541.3  677.35  1658.1  718.15  1726.2  747.52  1813.8  789.33  1852.7  801.91
#Mann= 3 , 0 , 0
       0      .1       0   996.8    .045       0  1113.3     .06       0
Bank Sta=996.8,1113.3
XS Rating Curve= 0 ,0
Exp/Cntr=0.3,0.1

Type RM Length L Ch R = 1 ,33830.2 ,825.6,847.6,869.5
XS GIS Cut Line= 4
     1899966.749      682810.346     1900578.728      682441.422
      1900921.61      682241.769     1901420.742      681985.693
#Sta/Elev= 30
       0  788.94     186  791.39   283.9  780.11   362.2  762.53   420.9  745.86
   489.4   720.8   577.5  693.55   626.5   680.8   830.7  671.24   917.8  657.88
   937.2   650.8   946.8  650.52  1004.9  651.61  1014.6  653.62  1024.3  658.38
    1063  683.33  1170.4  776.53  1180.2  782.06  1190.1  784.44  1229.5  789.52
  1268.8  789.37  1308.2  786.63  1396.8  774.52  1436.1  764.99  1455.8   757.6
  1465.7  756.39  1524.7  780.15  1544.4  785.32  1593.6  791.23  1672.3  797.15
#Mann= 3 , 0 , 0
       0      .1       0   917.8    .045       0  1024.3      .1       0
Bank Sta=917.8,1024.3
XS Rating Curve= 0 ,0
Exp/Cntr=0.3,0.1

Type RM Length L Ch R = 1 ,32982.6 ,906.9,902.5,898.2
XS GIS Cut Line= 4
     1899858.242       682875.45     1900474.561      682866.769
     1900808.763      683049.061     1901277.513      683240.033
#Sta/Elev= 30
       0  787.38   117.4  774.86   234.8  755.84   293.5  750.04   322.9  745.82
   459.8  710.47   538.1  685.71   557.7  681.75     587   678.4     714  671.52
   782.3  661.51   792.1  658.68   811.6  650.91   821.4   650.7   889.7     651
   899.4  653.78   909.2  659.85   928.7  674.85   938.5   680.6   967.8  693.04
   977.5  698.71  1113.9  781.46  1152.8  803.14  1211.2  841.78  1259.9  870.99
    1328  908.66  1337.8  912.14  1357.2  915.78  1386.4  917.75  1503.2  912.69
#Mann= 3 , 0 , 0
       0      .1       0   792.1    .045       0   909.2      .1       0
Bank Sta=792.1,909.2
XS Rating Curve= 0 ,0
Exp/Cntr=0.3,0.1

Type RM Length L Ch R = 1 ,32080.1 ,689.7,672.9,656.1
XS GIS Cut Line= 4
      1899511.02      683417.985     1899788.798       683504.79
     1900179.423      683617.637     1900743.659      683526.492
#Sta/Elev= 30
       0  920.13    38.8   916.4   106.7  889.24   116.4  883.76   164.9     846
     194  815.41   213.4  797.78   261.9  770.92   300.7   740.6   310.4  734.25
   358.8  707.64   416.9  669.66   426.6   664.8   455.6  655.23   465.3  651.63
   484.6   650.7   552.4  651.26   571.8  657.89   581.4  660.89   620.2  667.92
     717  680.94   746.1  686.75   765.4   693.3   901.1  748.46   978.6  775.47
  1085.1  803.38  1104.5  805.74  1133.6  804.35    1182  805.81  1269.2  797.12
#Mann= 3 , 0 , 0
       0      .1       0   455.6    .045       0   571.8      .1       0
Bank Sta=455.6,571.8
XS Rating Curve= 0 ,0
Exp/Cntr=0.3,0.1

Type RM Length L Ch R = 1 ,31407.1 ,908.2,908.5,908.4
XS GIS Cut Line= 4
     1899232.374      684588.124     1899721.957      684270.415
     1900117.791      684072.499     1900685.499      683780.832
#Sta/Elev= 30
       0  798.69    68.1  794.34   233.4  777.84   262.6  778.35     321  784.49
   389.1  787.88   408.5  788.01     428   785.2   457.2  776.18   466.9  771.36
   476.6  764.47   544.7  700.72   564.2  686.02   573.9  680.33   593.5  673.32
   652.5   661.5   672.2  655.14     682  652.07   701.6   650.7   780.3  650.92
   809.8  655.61     859  662.19   947.5  667.75  1104.7   689.3  1173.5  700.82
  1222.6  711.52  1291.3  733.45  1487.7  775.99  1595.7  787.56  1664.4  787.52
#Mann= 3 , 0 , 0
       0      .1       0   672.2    .045       0   809.8     .06       0
Bank Sta=672.2,809.8
XS Rating Curve= 0 ,0
Exp/Cntr=0.3,0.1

Type RM Length L Ch R = 1 ,30498.6 ,520,539.4,559.3
XS GIS Cut Line= 4
     1899518.832       684723.54     1900425.082      684843.332
     1900784.457       684661.04     1902221.957      683905.832
#Sta/Elev= 30
       0  888.35      59  885.91   108.1  879.93   314.5  824.64   481.6  758.07
   530.8  743.18   579.9   733.9   619.2  722.82   717.6  688.33   815.8  667.18
   884.6  668.09   963.3   659.2   982.9  650.22  1002.6   648.4    1091     653
  1110.7   660.1    1386  663.05  1484.4  678.36    1632  710.88  1720.6  716.89
  1828.8  714.81  2133.9  688.78    2193  689.53  2350.4   679.1  2389.8   679.1
  2527.6  699.79  2675.2  746.88  2763.8  788.75  2842.5  816.42  2940.9  861.44
#Mann= 3 , 0 , 0
       0     .08       0   963.3    .045       0  1110.7      .1       0
Bank Sta=963.3,1110.7
XS Rating Curve= 0 ,0
Exp/Cntr=0.3,0.1

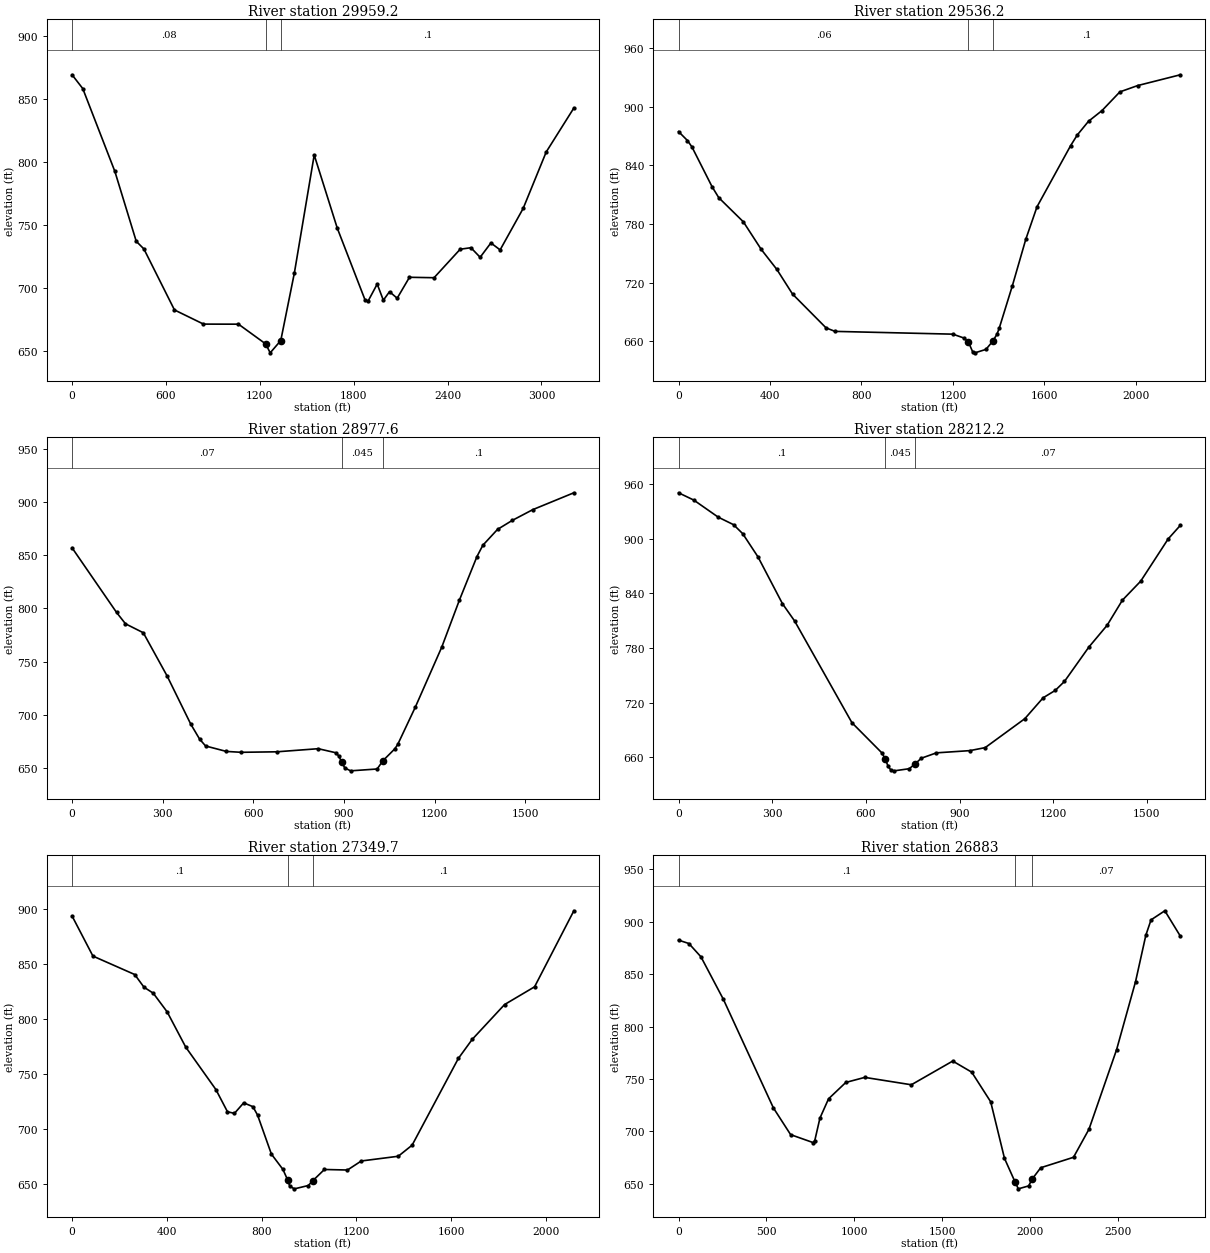
Type RM Length L Ch R = 1 ,29959.2 ,412,423,434.3
XS GIS Cut Line= 4
     1899430.291      684822.499     1900357.374       685129.79
     1900810.499      685322.499     1902419.874      685978.749
#Sta/Elev= 30
       0  869.43    68.4  858.46   273.5  792.62   410.2  737.05     459     731
   654.4   682.5     840  671.24  1063.6  671.18  1237.4  655.49  1266.3   648.4
  1333.9  658.18  1420.8  711.87  1547.6  805.68  1694.9  747.55  1871.7  690.72
  1891.3  689.39  1950.2  703.06  1989.5  690.22  2028.8  697.01  2077.9  691.82
  2156.4  708.46  2313.6  708.11  2480.5  730.75  2549.2  731.97  2608.1  724.35
  2676.9  735.75  2735.8  730.23  2883.1  763.19  3030.4  808.07  3207.1  843.01
#Mann= 3 , 0 , 0
       0     .08       0  1237.4    .045       0  1333.9      .1       0
Bank Sta=1237.4,1333.9
XS Rating Curve= 0 ,0
Exp/Cntr=0.3,0.1

Type RM Length L Ch R = 1 ,29536.2 ,549.3,558.5,565.9
XS GIS Cut Line= 4
     1899227.166      684905.832     1900169.874      685312.082
     1900440.707      685650.624     1900872.999      686244.374
#Sta/Elev= 30
       0  874.45    39.1  865.28    58.7  858.73   146.6  818.12     176  806.87
   283.5   782.2   361.7  754.02   430.2  733.49   498.6  708.37   645.2  673.82
   684.3  670.24  1199.9   667.4  1248.1  663.45  1267.4  659.55  1286.6   649.2
  1296.3  648.31  1344.4  651.83  1373.4  659.96  1392.6   667.3  1402.3  673.33
  1460.1  716.98  1518.8  764.47  1567.8  797.61  1714.7  860.05    1744  871.01
    1793  884.99  1851.8  895.87  1930.1  915.01  2008.4   921.5  2194.5   932.5
#Mann= 3 , 0 , 0
       0     .06       0  1267.4    .045       0  1373.4      .1       0
Bank Sta=1267.4,1373.4
XS Rating Curve= 0 ,0
Exp/Cntr=0.3,0.1

Type RM Length L Ch R = 1 ,28977.6 ,774.9,765.4,757.3
XS GIS Cut Line= 4
     1899149.041      684999.582     1899774.041       685442.29
     1899836.541      685707.915     1899930.291      686322.499
#Sta/Elev= 30
       0  856.85   147.3  796.16   176.8  785.52   235.7  777.13   314.2  736.72
   392.8  691.32   422.2  677.21   441.9  670.82   510.6  665.71   559.7  664.89
   677.5  665.36   814.6  668.28   873.1  664.45   882.9  661.35   892.6  655.44
   902.4  650.24   921.8  647.49  1009.6  649.23    1029   657.1  1067.9   668.1
  1077.6  672.24  1135.9  707.32  1223.4  763.66  1281.6  807.66  1339.9   848.7
  1359.4  859.28  1407.9  874.15  1456.5  882.55  1524.5  892.68  1660.5  908.52
#Mann= 3 , 0 , 0
       0     .07       0   892.6    .045       0    1029      .1       0
Bank Sta=892.6,1029
XS Rating Curve= 0 ,0
Exp/Cntr=0.3,0.1

Type RM Length L Ch R = 1 ,28212.2 ,865,862.5,859.7
XS GIS Cut Line= 4
     1898586.541      685296.457     1898862.582      685530.832
     1899164.666      685895.415     1899586.541      686541.249
#Sta/Elev= 30
       0   950.6    48.9  942.57   127.2   923.8   176.2  915.56   205.5  905.71
   254.5  880.16   332.8  828.79   371.8  809.77   555.4  698.04     652  664.66
   661.7  658.24   671.3  650.19     681  645.63   690.6  645.22     739  647.56
   758.3  653.13   777.6  659.08   825.9  664.98   933.2  667.42   982.1  670.73
    1109  702.49  1167.6  725.43  1206.6  733.59    1236  743.43  1314.1  781.15
  1372.6  805.09  1421.5  832.65  1480.1  853.52    1568  899.88    1607  914.81
#Mann= 3 , 0 , 0
       0      .1       0   661.7    .045       0   758.3     .07       0
Bank Sta=661.7,758.3
XS Rating Curve= 0 ,0
Exp/Cntr=0.3,0.1

Type RM Length L Ch R = 1 ,27349.7 ,465.1,466.7,468.2
XS GIS Cut Line= 4
     1898101.298      685556.874     1898326.992      686255.658
     1898700.256      686611.561     1899359.978      687175.797
#Sta/Elev= 30
       0  893.42    88.1  856.95   264.4  840.19   303.5  828.67   342.7   823.2
   401.4  806.21   479.8  774.16     607  735.59     656  715.35   685.4  713.88
   724.5  723.46   763.5  719.95     783  712.34   841.4  676.84     890  662.94
   909.5  653.56   919.2  647.51   938.7  645.23   997.1  648.24  1016.5  652.68
  1065.2  662.84  1162.5  662.35  1220.9  670.57  1376.9  674.87  1435.4  684.94
  1630.5   763.8    1689  781.16  1825.6  812.85  1952.4  829.02  2118.2  898.17
#Mann= 3 , 0 , 0
       0      .1       0   909.5    .045       0  1016.5      .1       0
Bank Sta=909.5,1016.5
XS Rating Curve= 0 ,0
Exp/Cntr=0.3,0.1

Type RM Length L Ch R = 1 ,26883   ,1103.5,1108.9,1114.2
XS GIS Cut Line= 4
     1896517.096       685871.11     1897938.971      686485.693
     1898329.596      686912.776     1898678.555      687548.193
#Sta/Elev= 30
       0  882.44    58.8   879.2   127.4  866.51   254.9  825.96   539.2  722.43
   637.2  696.92   764.7  689.36   774.5  691.23   803.9  712.69   852.9  731.09
     951   746.7  1058.8  751.52  1323.5  744.47  1558.8  767.09  1666.7  756.51
  1774.6  728.25  1853.1  674.26    1912  652.21  1931.6  645.22  1990.5  648.02
  2010.1  654.49  2059.1  665.35  2245.4  675.31  2333.5  702.12  2490.3  777.91
    2598  842.75  2656.8  887.19  2686.2  901.75  2764.6  910.42  2852.7  886.26
#Mann= 3 , 0 , 0
       0      .1       0    1912    .045       0  2010.1     .07       0
Bank Sta=1912,2010.1
XS Rating Curve= 0 ,0
Exp/Cntr=0.3,0.1