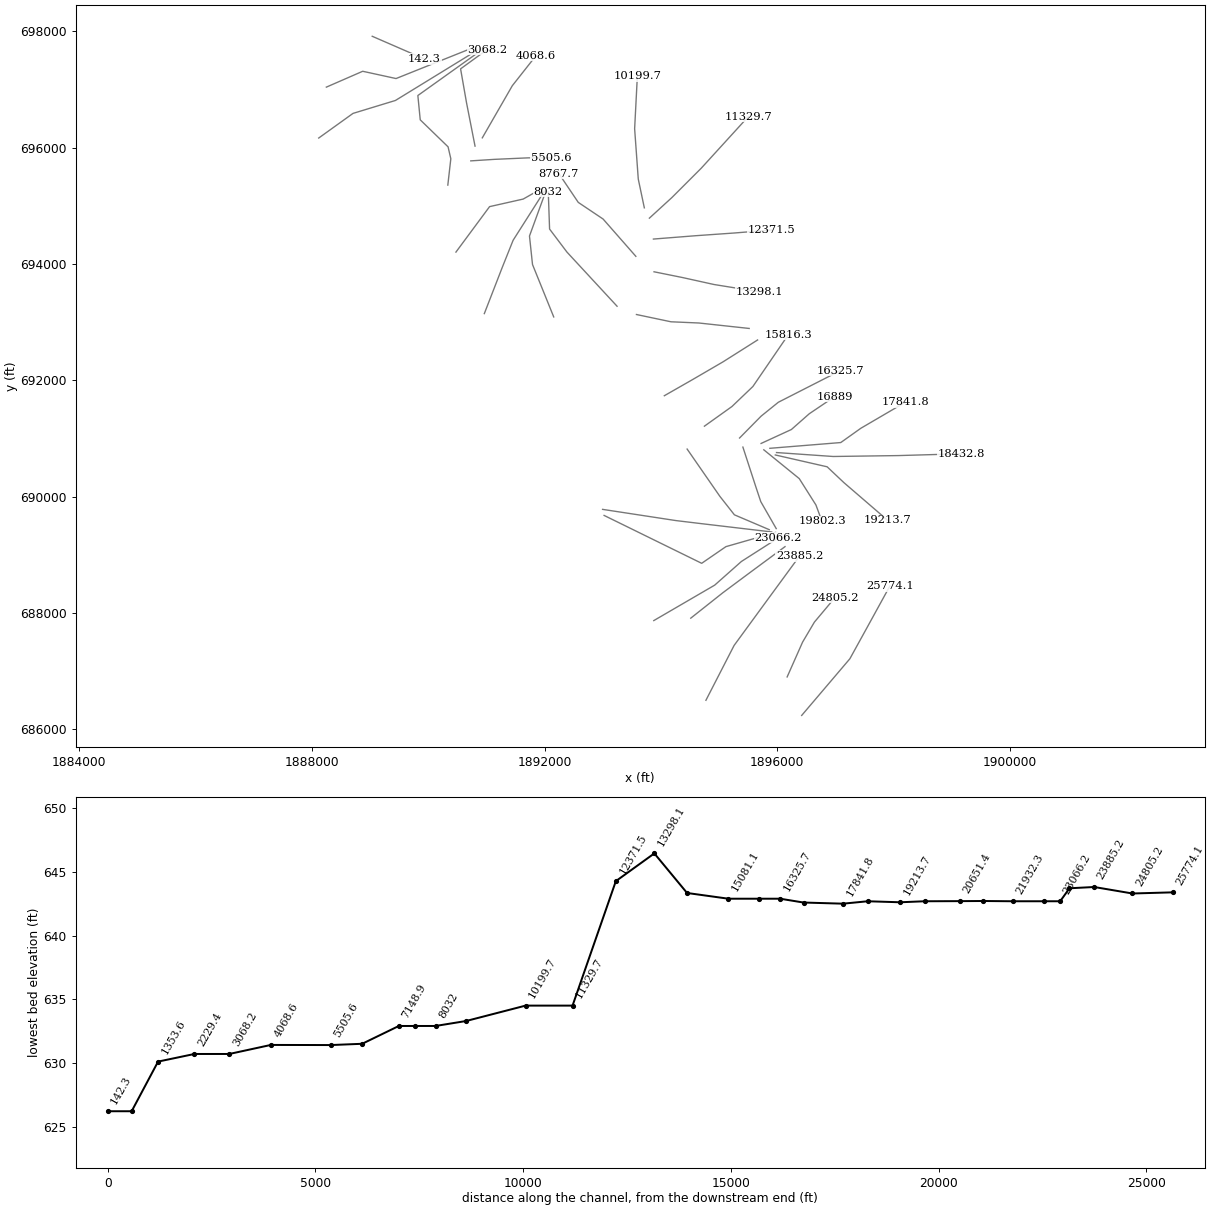
HEC-RAS study LtlKwhaRvr.prj: LtlKwhaRvr

--- LtlKwhaRvr.g01 (geometry) --- (continued)

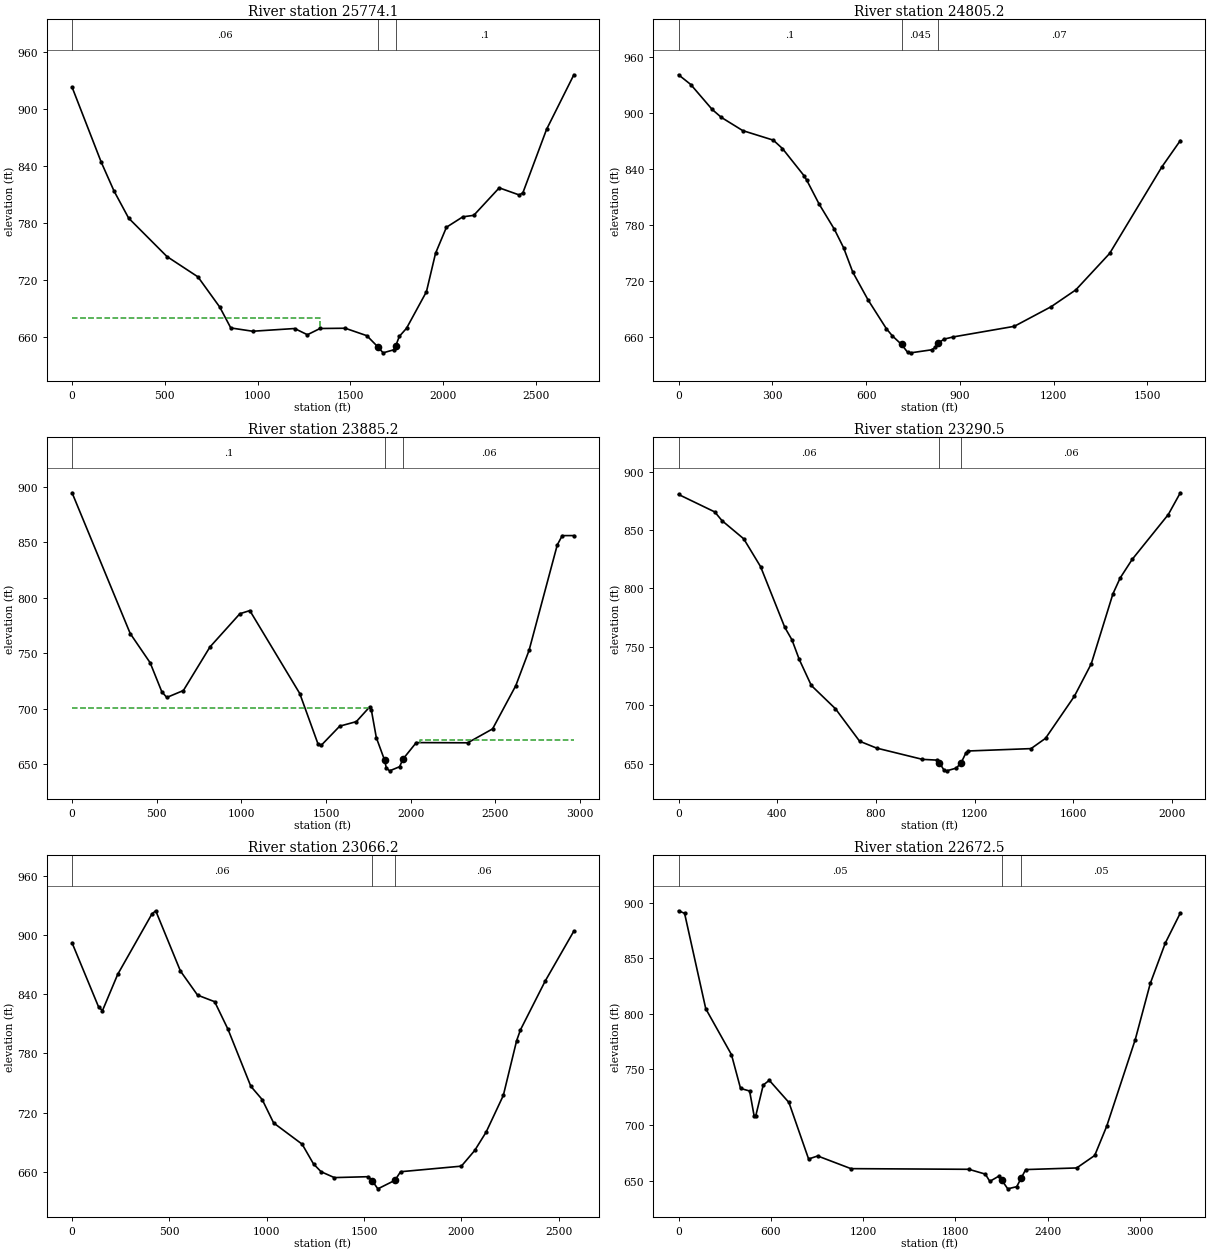
Type RM Length L Ch R = 1 ,25774.1 ,969.9,968.9,967.9
XS GIS Cut Line= 4
     1896418.138      686240.901     1897246.263       687214.86
     1897527.513      687725.276     1897933.763       688464.86
#Sta/Elev= 30
       0   923.4   157.4  844.24   226.2  813.93   304.9  785.38   511.4  744.91
   678.6  723.46   796.6  691.48   855.6  669.64   973.6  666.16  1199.8  669.03
  1268.6  662.48  1336.7  669.05  1472.7  669.32  1589.2  661.46  1647.5  649.86
  1676.7   643.4  1734.9  646.63  1744.6  650.72  1764.1  660.75  1802.9  669.26
  1910.3  707.82  1959.3  748.27  2018.2  775.77  2106.5  786.74  2165.4   788.3
  2302.7  817.28  2410.7  809.76  2430.3   812.1  2557.8  878.87    2705  936.43
#Mann= 3 , 0 , 0
       0     .06       0  1647.5    .045       0  1744.6      .1       0
#XS Ineff= 2 , 0
         1334.45  680.64
Permanent Ineff=
       F       F
Bank Sta=1647.5,1744.6
XS Rating Curve= 0 ,0
Exp/Cntr=0.3,0.1

Type RM Length L Ch R = 1 ,24805.2 ,921.8,920,918.1
XS GIS Cut Line= 4
     1896168.138       686902.36     1896433.763      687501.318
     1896636.888      687845.068     1896991.055      688266.943
#Sta/Elev= 30
       0  941.28    39.1  930.85   107.6  904.13   136.9  895.63   205.4  881.45
   303.2  871.22   332.5  862.22     401  833.33   410.7     828   449.8   802.7
   498.8  775.58   528.1  755.89   557.4  729.81   606.3  700.04     665  669.13
   684.4  661.39   713.6  652.25   733.1  643.78   742.9  643.31     811  646.63
   820.8  649.19   830.5  653.75     850  658.04   879.2  660.39  1074.2  671.73
  1192.2  692.79  1270.9  710.76  1379.1   749.8  1546.3  842.59  1605.3  870.78
#Mann= 3 , 0 , 0
       0      .1       0   713.6    .045       0   830.5     .07       0
Bank Sta=713.6,830.5
XS Rating Curve= 0 ,0
Exp/Cntr=0.3,0.1

Type RM Length L Ch R = 1 ,23885.2 ,601.5,594.7,588
XS GIS Cut Line= 4
     1894772.305      686501.318      1895256.68      687444.026
     1895866.055       688277.36      1896381.68      688980.485
#Sta/Elev= 30
       0  894.77   343.5  767.75   461.2  741.38   529.9  715.28   559.4  710.04
   657.5   716.3   814.5   755.6   991.2   785.6    1050  788.45    1345  713.61
  1453.2  667.92  1472.8     667    1581  684.14  1679.3  688.24  1757.9   701.5
  1767.8  698.85  1797.3  673.78  1846.4  653.35  1856.3  646.41  1875.9  643.82
  1934.9  647.55  1954.6  654.41  2033.2  669.31  2337.2  669.12  2484.1  681.68
  2621.3  720.74  2699.6  752.55  2866.2  847.71  2895.6  856.11  2964.2  856.14
#Mann= 3 , 0 , 0
       0      .1       0  1846.4    .045       0  1954.6     .06       0
#XS Ineff= 2 , 0
         1753.03  700.98 2055.93          671.71
Permanent Ineff=
       F       F
Bank Sta=1846.4,1954.6
XS Rating Curve= 0 ,0
Exp/Cntr=0.3,0.1

Type RM Length L Ch R = 1 ,23290.5 ,222.4,224.3,226.3
XS GIS Cut Line= 4
     1894511.888      687912.776     1895063.971      688350.276
     1895511.888       688683.61      1896131.68      689141.943
#Sta/Elev= 30
       0  880.46   146.8  865.49   176.1  858.03   264.2  842.46   332.6  818.58
   430.5  766.67   459.8  755.87   489.2  739.15   538.1  716.84   635.9  696.91
   733.8   669.1   802.4  663.23   988.5  653.55  1047.2   652.9    1057  650.74
  1076.6  644.08  1086.4  643.72  1125.6  646.05  1145.2   650.6  1164.8  659.12
  1174.6  660.73  1428.6  662.76  1487.2  671.55  1604.3  707.65  1672.6  735.37
  1760.4   795.3  1789.7  808.88  1838.4  824.81  1984.8  863.25  2033.6  881.89
#Mann= 3 , 0 , 0
       0     .06       0    1057    .045       0  1145.2     .06       0
Bank Sta=1057,1145.2
XS Rating Curve= 0 ,0
Exp/Cntr=0.3,0.1

Type RM Length L Ch R = 1 ,23066.2 ,396.6,393.7,390.9
XS GIS Cut Line= 4
     1893876.471       687871.11     1894923.346      688480.485
      1895381.68      688886.735     1896017.096      689292.985
#Sta/Elev= 30
       0  892.14   136.8  826.89   156.3  823.47   234.4  860.18   410.3  921.44
   429.8  924.67   556.8  863.55   644.7  839.14   732.6  832.47     801  804.54
   918.3  746.71   976.9  733.21  1035.5  709.53    1182  687.98  1240.5  667.94
  1279.4  660.06  1347.4   654.1  1522.4  655.02  1541.8  650.91    1571   642.7
  1658.5  651.32  1687.7  660.05  2000.1  665.71  2068.6  681.59  2127.4  700.28
  2215.6  737.43  2284.1  793.03  2303.7  803.96    2431  853.51    2578  904.07
#Mann= 3 , 0 , 0
       0     .06       0  1541.8    .045       0  1658.5     .06       0
Bank Sta=1541.8,1658.5
XS Rating Curve= 0 ,0
Exp/Cntr=0.3,0.1

Type RM Length L Ch R = 1 ,22672.5 ,756.3,740.2,723.7
XS GIS Cut Line= 4
     1893022.305      689678.401     1894699.388      688855.485
     1895116.055      689141.943     1895970.221      689386.735
#Sta/Elev= 30
       0  892.61    39.3  890.32     177  804.56   344.1  763.32   403.1  732.97
   462.1  730.62   491.6  708.12   501.4  707.92   550.6  735.96   589.9  740.26
   717.7  720.32   845.6  669.52   904.6  672.24  1120.9  660.85  1887.6  660.26
  1994.5  655.94  2023.7  649.41    2082  654.09  2101.5   650.5  2140.4   642.7
  2198.7  644.65  2227.9  652.41    2257  660.02  2588.6  661.48  2705.7  672.69
  2783.8  699.03  2969.4  776.92    3067  827.32  3164.6   863.6  3262.3  890.58
#Mann= 3 , 0 , 0
       0     .05       0  2101.5    .045       0  2227.9     .05       0
Bank Sta=2101.5,2227.9
XS Rating Curve= 0 ,0
Exp/Cntr=0.3,0.1

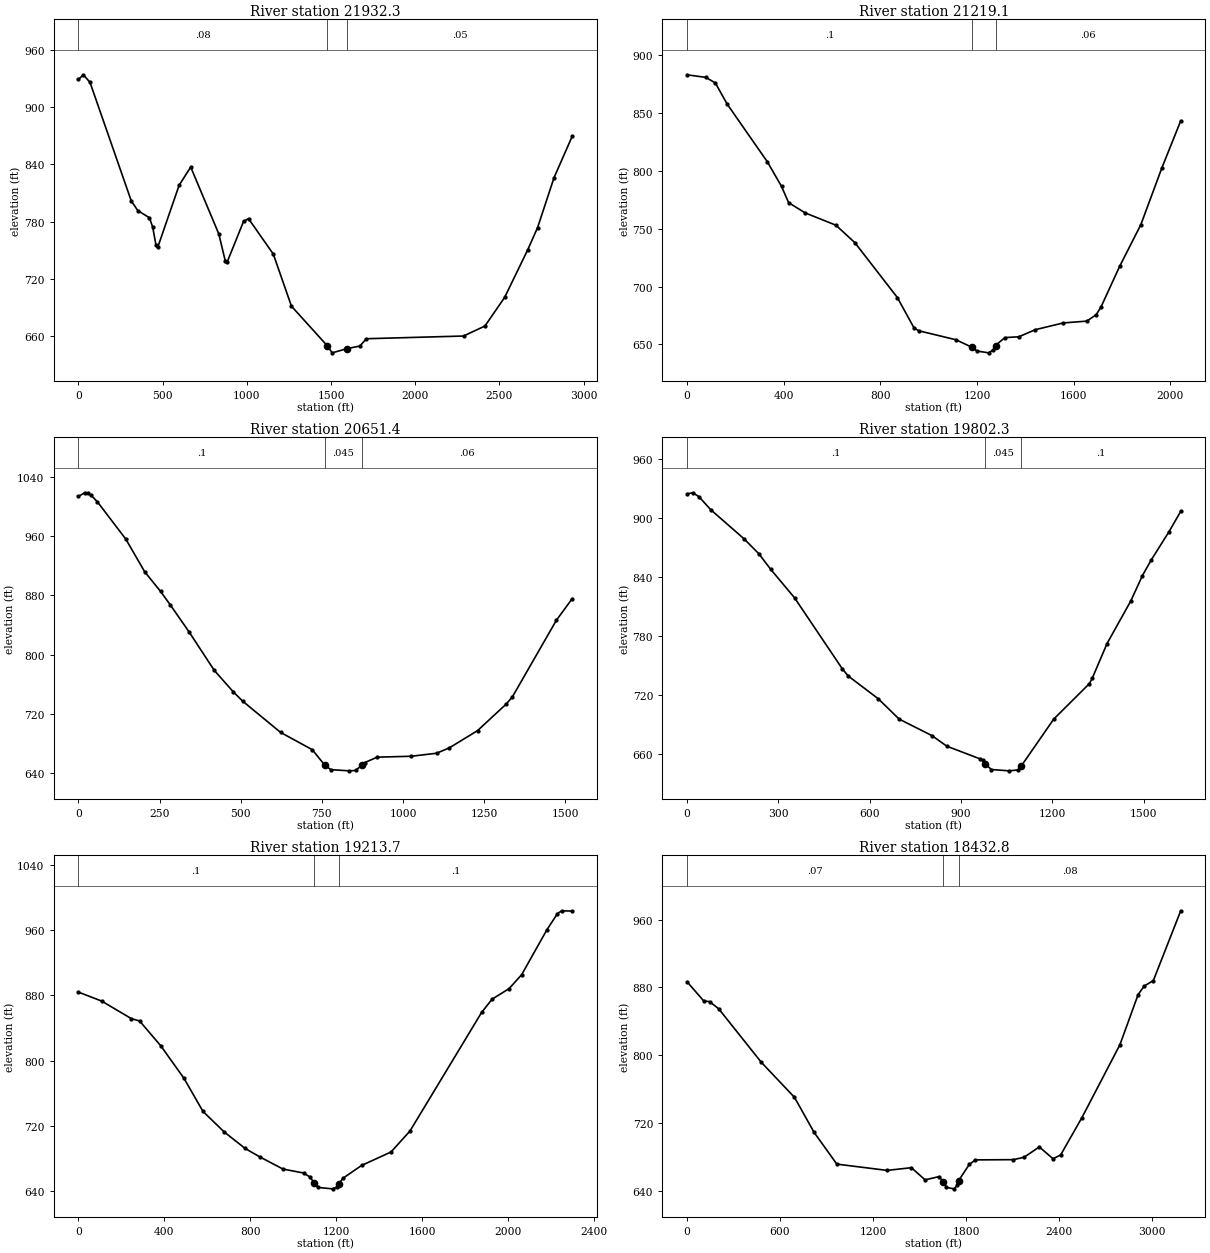
Type RM Length L Ch R = 1 ,21932.3 ,730.7,713.2,695.4
XS GIS Cut Line= 4
     1892996.263      689782.568      1894256.68       689589.86
     1894688.971      689537.776     1895902.513      689394.547
#Sta/Elev= 30
       0  929.03    29.4  933.94    68.7  926.04   313.9  801.81   353.1   791.6
   421.8   784.2   441.4   774.2     461  755.25   470.8  753.06   598.3   818.3
     667  837.29   833.7  767.28   872.9  738.43   882.7  737.47   980.8  780.34
  1010.2  783.28  1157.4  746.15  1265.3  691.56  1478.3  650.06  1507.3   642.7
  1594.4  647.03  1671.8  649.87  1710.5  657.48  2287.2  660.31  2414.3  670.77
  2531.6  700.85  2668.5  750.62  2727.2  773.93  2824.9  826.22  2932.4   869.4
#Mann= 3 , 0 , 0
       0     .08       0  1478.3    .045       0  1594.4     .05       0
Bank Sta=1478.3,1594.4
XS Rating Curve= 0 ,0
Exp/Cntr=0.3,0.1

Type RM Length L Ch R = 1 ,21219.1 ,575.8,567.8,559.8
XS GIS Cut Line= 4
     1894449.388      690819.026     1895011.888      690006.526
     1895261.888      689688.818     1895860.846       689433.61
#Sta/Elev= 30
       0  882.84    78.3  880.57   117.4  875.76   166.3  857.52   332.7  807.67
   391.4   786.4   420.7  772.39   489.2  763.56   616.4  752.95   694.7  737.87
   870.8  690.47   939.3  664.37   958.9  661.79  1113.3  654.01  1180.7  647.41
    1200  644.31  1248.1  642.72  1267.4  645.16    1277  649.04  1315.5  655.88
  1373.2  656.57  1441.1  662.68  1557.7  668.56  1654.9  670.11  1693.7  675.66
  1713.2  682.14  1790.9  717.45  1878.4  753.38  1965.8  802.56  2043.6  843.07
#Mann= 3 , 0 , 0
       0      .1       0  1180.7    .045       0    1277     .06       0
Bank Sta=1180.7,1277
XS Rating Curve= 0 ,0
Exp/Cntr=0.3,0.1

Type RM Length L Ch R = 1 ,20651.4 ,842.5,849,855.1
XS GIS Cut Line= 4
     1895407.721      690852.881     1895636.888      690149.756
     1895715.013      689915.381     1895980.638      689451.839
#Sta/Elev= 30
       0 1014.06    19.5    1019    29.2 1018.36    38.9 1015.71    58.4 1006.79
     146  956.28   204.3     912     253  885.52   282.2  867.78   340.6  830.88
   418.4  778.72   476.8  749.72     506  736.99   622.8  694.69   720.1   671.4
   758.5  650.61   777.5  644.29   834.6  642.71   853.6  643.19   872.6  650.04
   882.1   653.9   920.1  661.22  1025.4  662.45  1103.2  666.52    1142  673.69
  1229.4  697.12  1316.8  732.74  1336.3  742.52  1472.3  846.53  1520.8   875.6
#Mann= 3 , 0 , 0
       0      .1       0   758.5    .045       0   872.6     .06       0
Bank Sta=758.5,872.6
XS Rating Curve= 0 ,0
Exp/Cntr=0.3,0.1

Type RM Length L Ch R = 1 ,19802.3 ,582.6,588.6,594.9
XS GIS Cut Line= 4
     1895767.096      690806.006     1896376.471      690311.214
      1896662.93      689858.089     1896767.096      689576.839
#Sta/Elev= 30
       0  924.62    19.6   925.7    39.2   921.7    78.5  908.31   186.4   879.1
   235.5  863.79   274.7  847.87   353.2  818.77   510.2   746.4   529.8   739.1
     628  716.06   696.6  695.35   804.4  678.52   853.2  667.77   960.4  655.08
   970.2  653.23   979.9   649.4   999.4  644.04  1057.9   642.7  1087.1  643.62
  1096.9  647.36  1204.1  695.38    1321  731.41  1330.7  737.05  1379.1  772.28
  1456.5  815.26  1495.2  841.37  1524.2  857.36  1582.3  885.95    1621  906.82
#Mann= 3 , 0 , 0
       0      .1       0   979.9    .045       0  1096.9      .1       0
Bank Sta=979.9,1096.9
XS Rating Curve= 0 ,0
Exp/Cntr=0.3,0.1

Type RM Length L Ch R = 1 ,19213.7 ,764.7,780.9,797.1
XS GIS Cut Line= 4
     1895965.013      690717.464     1896855.638      690514.339
     1897142.096      690243.506     1897892.096      689597.672
#Sta/Elev= 30
       0  883.86     108  872.94   245.6  851.47   284.8  848.45   383.1  818.08
   491.1  778.19   579.5  737.62   677.8  712.51     776  692.11   844.7  681.69
     952  666.88  1048.1  662.02    1077  657.21  1096.2  650.25  1115.4  644.29
  1182.7  642.62    1202  644.78  1211.6  648.56  1230.8  655.59  1317.5  671.28
  1454.7  687.82  1542.9  713.55  1876.1  858.93  1925.1  875.27  2003.5  888.06
  2062.3  905.15  2179.9  960.31  2228.9  980.03  2248.5  983.64  2297.5  983.27
#Mann= 3 , 0 , 0
       0      .1       0  1096.2    .045       0  1211.6      .1       0
Bank Sta=1096.2,1211.6
XS Rating Curve= 0 ,0
Exp/Cntr=0.3,0.1

Type RM Length L Ch R = 1 ,18432.8 ,579.1,591,603.9
XS GIS Cut Line= 4
     1895985.846      690759.131     1896959.805      690691.422
     1898079.596      690707.047     1899168.138      690738.297
#Sta/Elev= 30
       0  886.82   107.4  864.24   146.4  863.22     205  854.81   478.4  792.03
   693.2  750.59   820.1  709.21   966.6  671.83  1290.7  664.44  1447.8  667.62
  1536.3  653.26  1624.7  657.06  1654.1  650.81  1673.8  644.38  1722.9   642.7
  1742.6  646.66  1752.4  652.45  1821.2  671.46  1860.4  676.82    2106  677.09
  2174.7  679.94  2272.8  692.08  2361.1  678.23  2410.2  682.54  2547.5  726.54
  2792.8  812.46  2910.5  871.67  2949.7  881.68  3008.6  888.16  3185.2  970.38
#Mann= 3 , 0 , 0
       0     .07       0  1654.1    .045       0  1752.4     .08       0
Bank Sta=1654.1,1752.4
XS Rating Curve= 0 ,0
Exp/Cntr=0.3,0.1

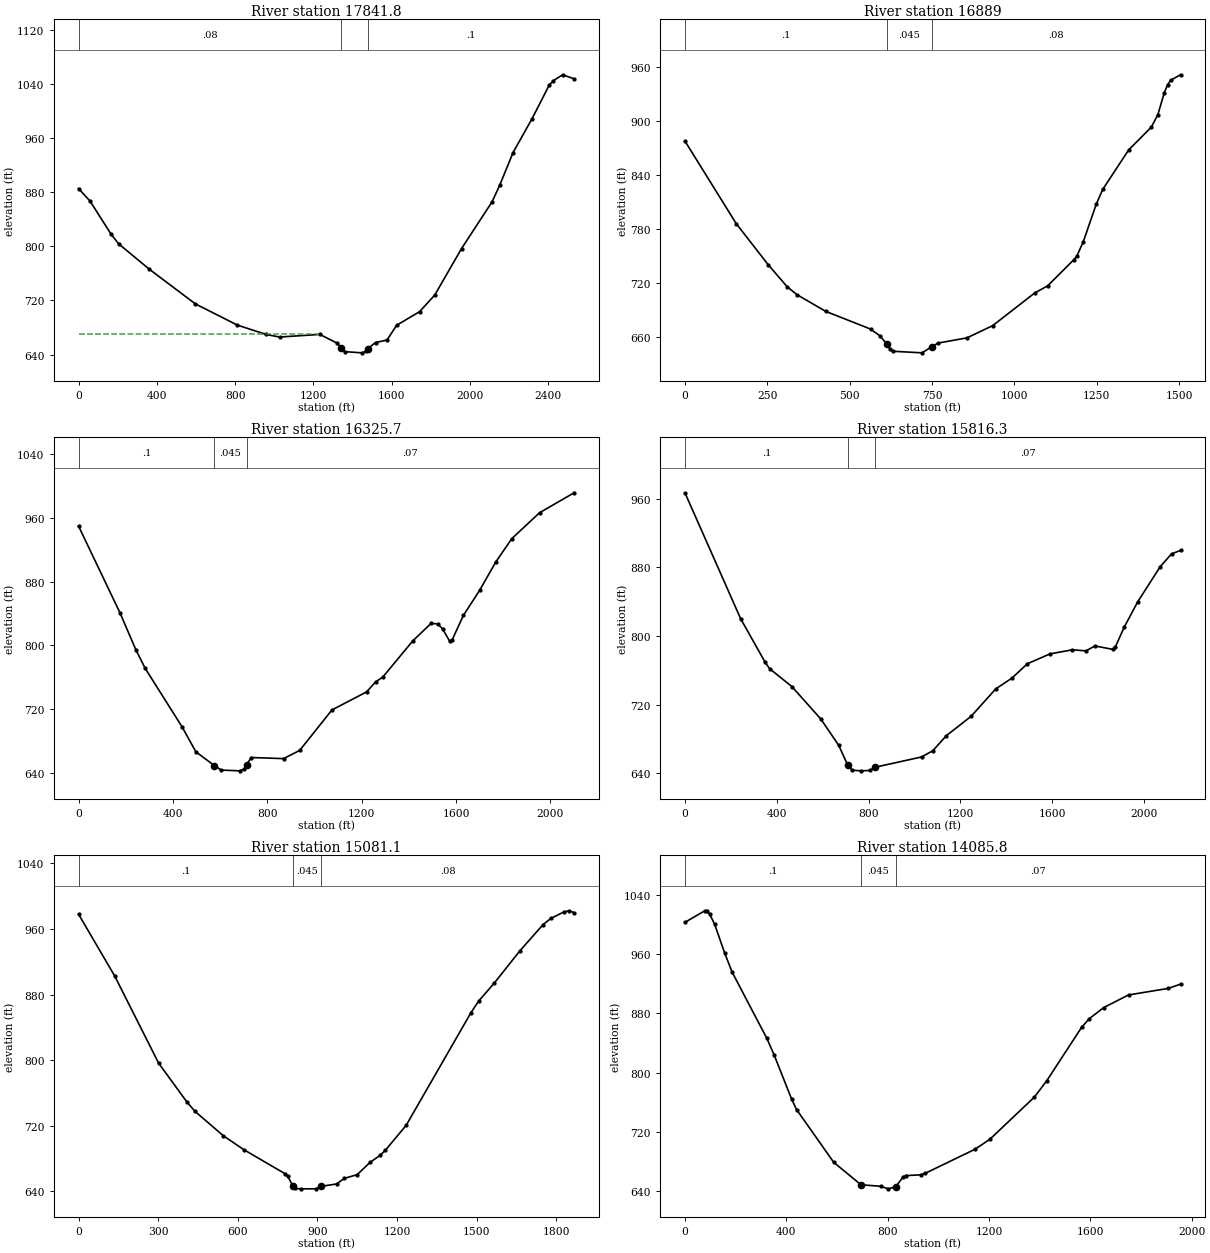
Type RM Length L Ch R = 1 ,17841.8 ,950.4,952.8,954.1
XS GIS Cut Line= 4
     1895871.263      690832.047     1897090.013      690931.006
     1897433.763      691175.797     1898199.388      691623.714
#Sta/Elev= 30
       0  885.46    58.7  867.02   166.3  817.98   205.4  803.62   361.9  766.13
   596.7  714.95   811.9  683.49   958.6  669.69  1027.1  665.89  1232.6  669.74
  1320.9   656.9  1340.5   650.3  1360.2  644.25  1448.5  642.51  1468.1   644.8
  1477.9  648.79  1517.2  657.75  1576.1  661.51  1625.1  683.28  1742.2  703.35
  1820.2  728.12  1956.7  796.77  2112.6  865.82  2151.6  890.31  2219.9  938.73
  2317.3  989.05  2405.1 1038.67  2424.6 1044.86  2473.3 1053.73  2531.8 1047.76
#Mann= 3 , 0 , 0
       0     .08       0  1340.5    .045       0  1477.9      .1       0
#XS Ineff= 2 , 0
         1224.08  669.66
Permanent Ineff=
       F       F
Bank Sta=1340.5,1477.9
XS Rating Curve= 0 ,0
Exp/Cntr=0.3,0.1

Type RM Length L Ch R = 1 ,16889   ,562.9,563.3,563.6
XS GIS Cut Line= 4
     1895720.221      690915.381     1896241.055      691154.964
     1896548.346      691425.797     1896980.638      691717.464
#Sta/Elev= 30
       0  877.87   155.5  786.25   252.6  740.53   310.9  715.81   340.1  707.23
   427.5  688.63   563.6  668.99   592.8  661.25   612.3  652.53   622.1  646.59
   631.8  644.34   719.6   642.6   748.8  649.27   768.4  653.45   856.1  659.23
   934.1  672.81  1061.6  709.06    1101  717.02  1179.7  745.78  1189.5  749.92
  1209.2  766.06  1248.6  807.78  1268.2  824.13    1347  868.04  1415.8  893.34
  1435.5  907.14  1455.2  931.66    1465  940.37  1474.9   945.5  1504.4  951.46
#Mann= 3 , 0 , 0
       0      .1       0   612.3    .045       0   748.8     .08       0
Bank Sta=612.3,748.8
XS Rating Curve= 0 ,0
Exp/Cntr=0.3,0.1

Type RM Length L Ch R = 1 ,16325.7 ,507,509.4,511.8
XS GIS Cut Line= 4
      1895350.43      691009.131     1895720.221      691384.131
     1896017.096      691623.714     1897079.596      692165.381
#Sta/Elev= 30
       0  949.67   175.6  840.99   243.8  794.09   282.8  771.21   438.9  698.07
   497.4  666.77   575.6  649.52   604.9  643.86   683.2   642.9   702.7  645.12
   712.5  650.45   732.1  659.59     869  658.22   937.5  668.48  1074.3  719.21
    1221  741.79  1260.1  754.59  1289.4  760.22  1416.5   805.6  1494.7  827.72
    1524  826.92  1543.6  820.54  1572.9  805.56  1582.7  806.29  1631.5  837.67
    1700  868.96  1768.4  904.41  1836.8  933.93  1954.1  966.25  2100.8  991.31
#Mann= 3 , 0 , 0
       0      .1       0   575.6    .045       0   712.5     .07       0
Bank Sta=575.6,712.5
XS Rating Curve= 0 ,0
Exp/Cntr=0.3,0.1

Type RM Length L Ch R = 1 ,15816.3 ,740.9,735.2,730.3
XS GIS Cut Line= 4
     1894746.263      691212.256     1895220.221      691550.797
     1895579.596      691894.547     1896188.971      692785.172
#Sta/Elev= 30
       0  966.92   242.7  820.17   349.5  769.35   368.9  761.93     466  741.08
   592.2  703.18   670.2  672.49   709.2  649.43   728.7  643.63   767.7   642.9
   806.7  643.38   826.2  646.96    1031   659.1  1079.8  666.32  1138.6  683.84
  1246.5  706.42  1354.4  738.52  1423.1  750.65  1491.8  767.72  1589.9  779.14
    1688  783.97  1746.9  782.68  1786.1  788.45  1864.6  784.38  1874.4  787.02
  1913.6  810.38  1972.5  839.94  2070.6  880.92  2119.7   895.7  2158.9  899.79
#Mann= 3 , 0 , 0
       0      .1       0   709.2    .045       0   826.2     .07       0
Bank Sta=709.2,826.2
XS Rating Curve= 0 ,0
Exp/Cntr=0.3,0.1

Type RM Length L Ch R = 1 ,15081.1 ,1007.7,995.3,982
XS GIS Cut Line= 4
     1894057.461      691735.693     1894531.419      692006.526
     1895067.877      692319.026     1895660.325      692694.026
#Sta/Elev= 30
       0  978.07   136.5  902.53   302.2   796.1   409.4  748.49   438.7  737.55
   545.9  707.62   623.5   690.6   778.7   661.3   788.4  658.28   807.8   646.5
   817.5  643.35   836.9   642.9   895.1  642.94   914.5  645.95   972.7  648.84
  1001.8  655.67  1050.3  660.21  1098.8  675.17  1137.6  683.99    1157  690.13
  1234.9   720.4  1478.4  857.45  1507.6   871.8    1566  893.56  1663.4  933.24
    1751  965.33  1780.2  972.83  1828.9  980.65  1848.4  982.15  1867.9  979.85
#Mann= 3 , 0 , 0
       0      .1       0   807.8    .045       0   914.5     .08       0
Bank Sta=807.8,914.5
XS Rating Curve= 0 ,0
Exp/Cntr=0.3,0.1

Type RM Length L Ch R = 1 ,14085.8 ,791.2,787.7,784.6
XS GIS Cut Line= 4
     1893578.294      693131.526     1894172.044      693006.526
     1894651.211      692985.693     1895515.794      692891.943
#Sta/Elev= 30
       0 1002.88    78.3  1018.5    88.1 1017.69    97.9  1013.9   117.4 1000.14
   156.6  961.75   185.9  935.95     323  846.57   352.3  823.76   420.8  764.62
   440.4  750.38   587.2  679.13   694.9  648.84   773.2  646.79   802.5  643.35
   831.9  646.16   861.3  659.46     871  661.21   929.8  662.23   949.4  664.47
    1145  696.77  1203.6  710.24  1379.5  767.26  1428.4  789.37  1565.2  861.05
  1594.5  872.53  1653.1  887.98  1750.8  904.96  1907.2  913.72    1956   919.5
#Mann= 3 , 0 , 0
       0      .1       0   694.9    .045       0   831.9     .07       0
Bank Sta=694.9,831.9
XS Rating Curve= 0 ,0
Exp/Cntr=0.3,0.1

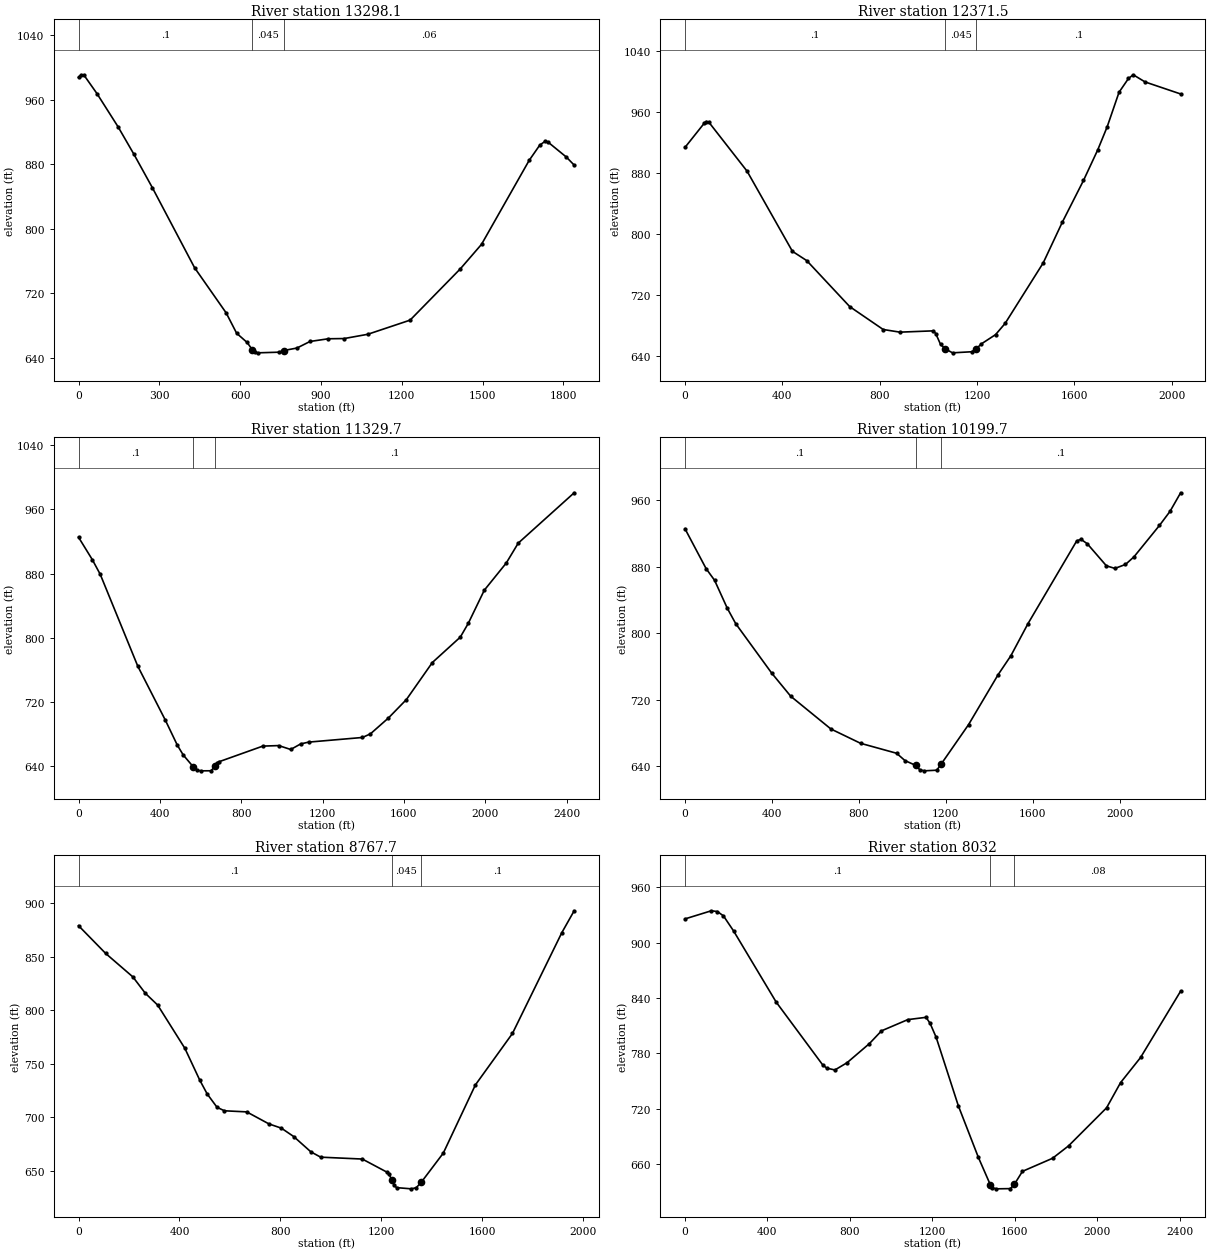
Type RM Length L Ch R = 1 ,13298.1 ,920.5,926.6,932.3
XS GIS Cut Line= 4
     1893880.377      693865.901     1894369.961      693766.943
     1894911.627      693647.151     1895687.669      693522.151
#Sta/Elev= 30
       0  987.42     9.8  990.66    19.6  990.55    68.6  967.35   146.9  926.24
   205.7  892.29   274.2  850.91   430.9  751.85   548.2   695.9   587.1  670.71
     626  659.31   645.5  650.29   655.2  647.03   664.9  646.46   742.8  647.25
   762.3  649.34   810.9   652.4   859.6  660.54   927.7  663.88   986.1  664.14
  1073.9  669.42  1231.1  686.94  1417.8  750.49  1496.4   780.8  1673.2  884.69
  1712.6   903.6  1732.2  908.24    1742  907.65  1810.8  888.94  1840.3  878.88
#Mann= 3 , 0 , 0
       0      .1       0   645.5    .045       0   762.3     .06       0
Bank Sta=645.5,762.3
XS Rating Curve= 0 ,0
Exp/Cntr=0.3,0.1

Type RM Length L Ch R = 1 ,12371.5 ,1025.7,1041.8,1057.9
XS GIS Cut Line= 4
     1893869.961      694428.401     1894593.919      694485.693
     1895260.586      694532.568     1895901.211      694584.651
#Sta/Elev= 30
       0  913.46    78.5   944.9    88.3  947.42    98.1  946.53   255.2  882.34
   441.6  777.32   500.5  765.13   677.2  704.85   814.7  674.86   883.5  671.39
  1021.1  673.11  1030.9  669.43  1050.6  655.22  1070.2  649.49  1099.7  644.28
  1178.3   645.7    1198  649.71  1217.6  655.88  1276.6  668.14  1315.9  682.86
  1472.4  762.11  1550.4  815.11    1638  870.16  1696.4  910.12  1735.4  940.49
  1784.1  985.74    1823 1003.85  1842.5 1008.66  1891.2  999.26  2037.3  983.51
#Mann= 3 , 0 , 0
       0      .1       0  1070.2    .045       0    1198      .1       0
Bank Sta=1070.2,1198
XS Rating Curve= 0 ,0
Exp/Cntr=0.3,0.1

Type RM Length L Ch R = 1 ,11329.7 ,1110.7,1130,1149.4
XS GIS Cut Line= 4
     1893800.516      694787.776     1894187.669      695141.943
     1894692.877      695647.151     1895500.169      696532.568
#Sta/Elev= 30
       0  925.35      68  897.37   106.9  879.11   291.5  764.77   427.5  697.35
   485.8  666.53     515  654.22   563.9  639.64   583.4  635.23     603   634.5
     652  634.58   671.5   640.4   681.3  644.37   691.1  645.85   906.4   665.3
   984.7  665.94  1043.4  661.09  1092.4     668  1131.5  670.26  1396.3  676.04
  1435.6  680.56    1524  700.28  1612.4  723.25  1740.1  769.37  1877.6  801.01
  1916.8  818.16  1995.4  859.36  2103.5  893.24  2162.4     918  2437.4  980.68
#Mann= 3 , 0 , 0
       0      .1       0   563.9    .045       0   671.5      .1       0
Bank Sta=563.9,671.5
XS Rating Curve= 0 ,0
Exp/Cntr=0.3,0.1

Type RM Length L Ch R = 1 ,10199.7 ,1411.4,1432,1452.6
XS GIS Cut Line= 4
     1893713.711       694964.86     1893609.544      695459.651
     1893547.044      696324.235     1893593.919      697230.485
#Sta/Elev= 30
       0  925.98    97.2  877.94   136.1  863.93   194.5  830.32   233.4   811.7
   398.7  752.22   486.2  724.36   671.2  684.88   807.6  667.66   973.2  655.68
  1012.1  646.82  1060.8  641.13  1080.3  635.75  1099.8   634.5  1158.2  635.26
  1177.7  642.36  1304.3  690.09  1440.8  750.44  1499.3  773.18  1577.4  811.56
  1801.8  911.27  1821.3  913.29  1850.6  907.88  1938.4  881.36  1977.4  878.21
  2026.2  882.96  2065.3  892.16  2182.4  929.91  2231.2  946.94  2279.9  969.27
#Mann= 3 , 0 , 0
       0      .1       0  1060.8    .045       0  1177.7      .1       0
Bank Sta=1060.8,1177.7
XS Rating Curve= 0 ,0
Exp/Cntr=0.3,0.1

Type RM Length L Ch R = 1 ,8767.7  ,743.1,735.7,728
XS GIS Cut Line= 4
     1893567.877      694131.526     1893005.377      694772.151
     1892578.294       695058.61     1892244.961      695553.401
#Sta/Elev= 30
       0  878.87   107.8  852.91   215.6     831   264.6   815.8   313.6  804.76
   421.4  764.36   480.2  734.78   509.6  721.87   548.8  709.36   578.2  706.12
   666.3   705.1   754.5  693.86   803.5  689.92   852.5  682.08   920.4  667.81
   959.3  662.84  1124.2  661.09  1221.2  648.93  1230.9   646.8  1240.6  641.66
  1250.4  636.58    1260  634.42  1318.3  633.29  1337.7  634.33  1357.1  639.24
    1445  666.64  1572.2  730.29  1718.9  778.27  1914.5  872.33  1963.4  892.76
#Mann= 3 , 0 , 0
       0      .1       0  1240.6    .045       0  1357.1      .1       0
Bank Sta=1240.6,1357.1
XS Rating Curve= 0 ,0
Exp/Cntr=0.3,0.1

Type RM Length L Ch R = 1 ,8032    ,512.8,500.4,488.2
XS GIS Cut Line= 4
     1893244.961      693273.887      1892383.85      694204.443
     1892085.239      694600.276     1892062.669      695240.901
#Sta/Elev= 30
       0  925.89   127.8  934.72   157.2  933.91   186.7  929.18   235.9   912.8
   442.3  835.67   668.3  767.38     688  763.92   727.3  761.92   786.3  769.79
   894.4  790.47   953.4  804.39  1081.1  816.58  1169.6  819.07  1189.2  812.53
  1218.7  797.32  1326.2  723.05  1423.4  667.05  1481.7  637.18  1491.5   634.1
  1510.9   632.9    1579  633.15  1598.4  637.94  1637.3  651.88  1783.1  666.04
  1860.8  679.51  2045.4  720.84  2113.3  748.18  2210.5   775.5  2404.7  847.47
#Mann= 3 , 0 , 0
       0      .1       0  1481.7    .045       0  1598.4     .08       0
Bank Sta=1481.7,1598.4
XS Rating Curve= 0 ,0
Exp/Cntr=0.3,0.1

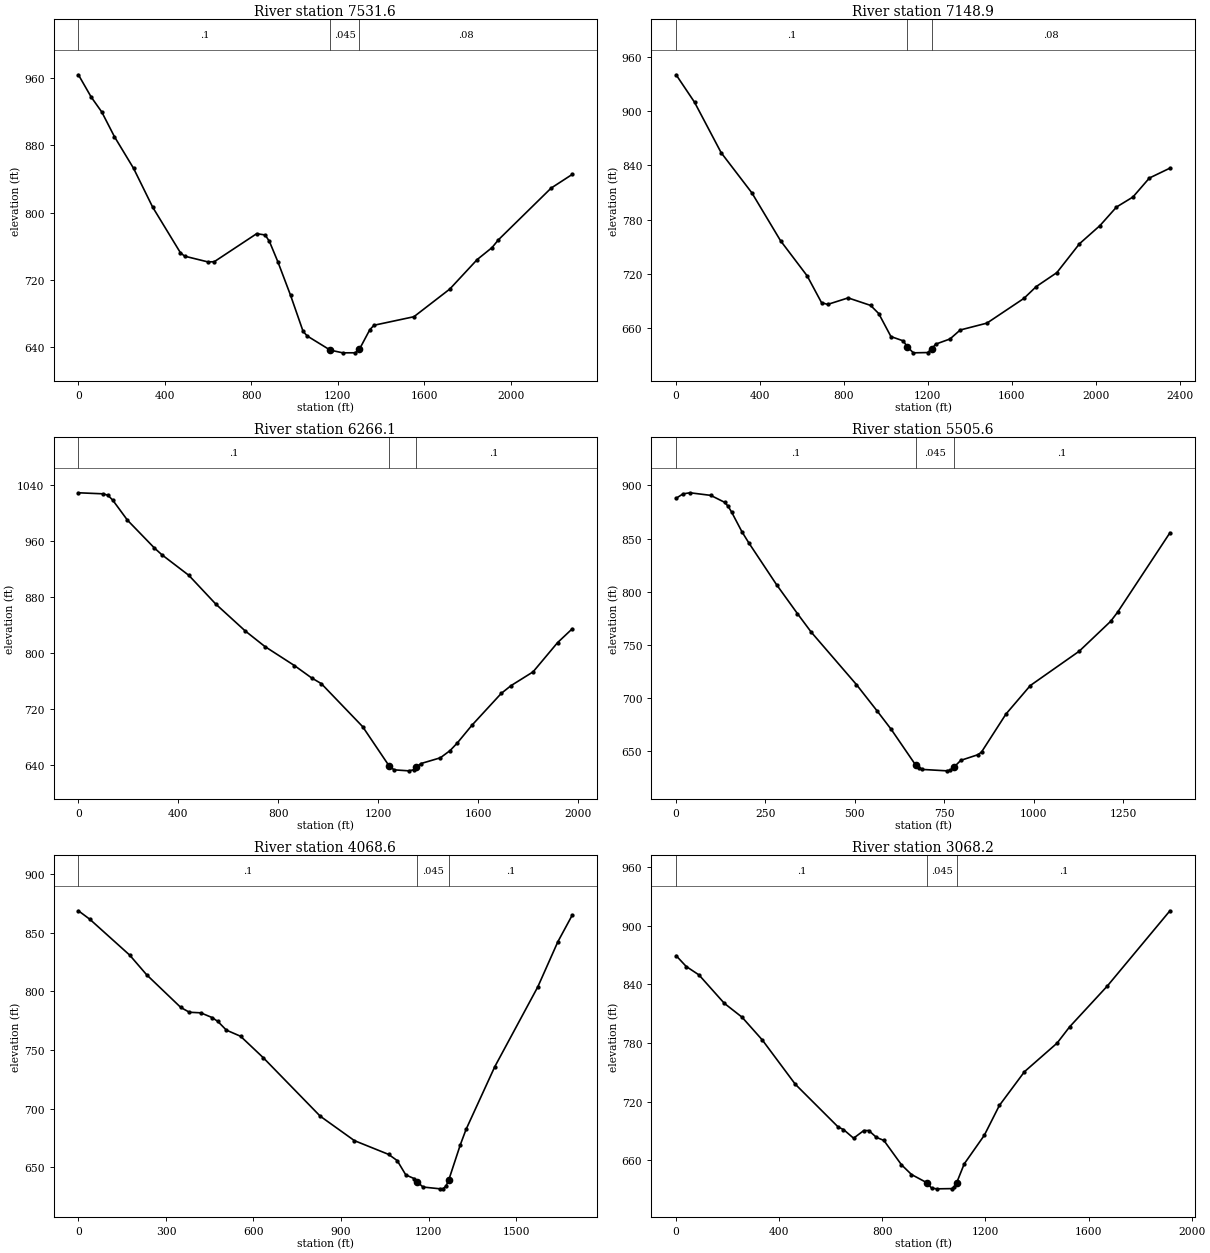
Type RM Length L Ch R = 1 ,7531.6  ,393.6,382.6,371.6
XS GIS Cut Line= 4
     1892156.419       693089.86     1891791.836      693990.901
     1891739.752      694480.485     1892021.002      695251.318
#Sta/Elev= 30
       0  964.04    58.9   937.6     108  919.75   166.9  890.22   255.3  852.57
   343.6  806.38   471.3  752.39   490.9  748.07   598.9   741.2   628.4   741.4
   824.7  774.79     864  773.28   883.6  765.66   922.9  741.29   981.7  701.32
  1039.6  658.44  1058.9  652.93  1165.1  636.14    1223   632.9  1280.9  632.96
  1300.2  637.19  1348.5  660.55  1367.8  665.76  1552.3   675.9  1718.3  708.85
  1845.3  744.04  1913.7  758.23    1943  767.43  2187.2  829.09  2284.9   845.4
#Mann= 3 , 0 , 0
       0      .1       0  1165.1    .045       0  1300.2     .08       0
Bank Sta=1165.1,1300.2
XS Rating Curve= 0 ,0
Exp/Cntr=0.3,0.1

Type RM Length L Ch R = 1 ,7148.9  ,904.3,882.9,861.4
XS GIS Cut Line= 4
     1890963.711      693147.151     1891271.002      693938.818
     1891458.502      694407.568     1891994.961      695251.318
#Sta/Elev= 30
       0  939.83    87.8  909.51   214.7   853.8   361.2  809.46   497.8  756.64
   624.7  717.84     693  688.36   722.3  686.34   819.9  693.54   926.9  685.27
   965.7  676.27    1024  650.86  1082.2  646.15  1101.6  639.74  1130.8   632.9
  1198.7  633.22  1218.2  637.36  1237.6  642.52  1305.5  648.21  1354.1   658.1
  1481.5   665.7    1658  693.03  1716.8  706.08  1814.8  721.43  1922.6  753.28
  2020.6  773.43  2099.1  793.83  2177.5  804.91  2255.9  825.86  2353.9  836.77
#Mann= 3 , 0 , 0
       0      .1       0  1101.6    .045       0  1218.2     .08       0
Bank Sta=1101.6,1218.2
XS Rating Curve= 0 ,0
Exp/Cntr=0.3,0.1

Type RM Length L Ch R = 1 ,6266.1  ,765,760.5,755.8
XS GIS Cut Line= 4
     1890475.864      694204.443     1891053.989      694985.693
     1891632.114      695115.901     1891989.752      695319.026
#Sta/Elev= 30
       0 1028.83    98.2 1027.34   117.8 1025.38   137.4 1018.28   196.3  989.63
   304.3  949.83   333.8  940.32   441.8  910.85   549.8  869.72   667.6  831.34
   746.1  809.15   863.9  782.02   932.6  764.39   971.9  756.09    1137  694.74
  1243.9   638.1  1263.3  632.91  1321.6   631.5  1341.1     633  1350.8  636.32
  1370.2  641.88  1447.9   650.1  1486.8  660.38  1515.9  671.31  1574.3  696.58
  1691.8  742.16    1731  753.28  1819.1  772.94    1917  814.68  1975.8  834.46
#Mann= 3 , 0 , 0
       0      .1       0  1243.9    .045       0  1350.8      .1       0
Bank Sta=1243.9,1350.8
XS Rating Curve= 0 ,0
Exp/Cntr=0.3,0.1

Type RM Length L Ch R = 1 ,5505.6  ,1417.1,1437,1456.1
XS GIS Cut Line= 4
     1890731.072      695772.151     1891137.322      695798.193
     1891720.655      695824.235      1892111.28      695824.235
#Sta/Elev= 30
       0  887.97    19.4  892.12    38.8  893.14    96.9   890.7   135.7  884.16
   145.4  880.49   155.1  875.07   184.2  856.42   203.5  845.92   281.1   806.6
   339.2  779.49     378  761.97   504.4  712.64   562.8  687.59   601.7  670.48
   669.8  637.01   679.6  633.95   689.3  632.72   757.4   631.4   767.2  632.02
   776.9  634.74   796.4  641.26     845  646.65   854.8  649.29   922.9  684.89
     991  711.71  1127.7  743.99  1215.6   772.1  1235.1  780.71  1381.6  855.49
#Mann= 3 , 0 , 0
       0      .1       0   669.8    .045       0   776.9      .1       0
Bank Sta=669.8,776.9
XS Rating Curve= 0 ,0
Exp/Cntr=0.3,0.1

Type RM Length L Ch R = 1 ,4068.6  ,981.4,1000.5,1019.5
XS GIS Cut Line= 3
     1890928.989      696167.985     1891444.614      697063.818
       1891852.6      697581.179
#Sta/Elev= 30
       0  868.84      39  861.61   175.5  831.04     234  814.16     351  786.27
   380.3   782.2   419.3   781.7   458.3  777.66   477.8  774.36   507.1  766.93
   555.8  761.69   633.8  743.32   828.8  693.44   945.9  672.57  1063.1  660.82
  1092.6  655.53  1122.1  643.29  1151.6  640.08  1161.5  637.26  1181.1  632.95
  1240.1  631.41    1250  631.58  1259.8  633.76  1269.6  639.24    1309   669.1
  1328.6  682.18    1427  735.69  1574.5  803.89  1643.3  842.44  1692.5  865.13
#Mann= 3 , 0 , 0
       0      .1       0  1161.5    .045       0  1269.6      .1       0
Bank Sta=1161.5,1269.6
XS Rating Curve= 0 ,0
Exp/Cntr=0.3,0.1

Type RM Length L Ch R = 1 ,3068.2  ,840.8,838.8,836.6
XS GIS Cut Line= 4
     1890803.989      696025.624     1890658.155      696768.679
     1890555.725      697353.749     1891012.322      697685.346
#Sta/Elev= 30
       0  869.21    39.3  858.12    88.5  849.55   186.8   820.5   255.7  806.28
   334.4  782.95   462.2  737.71   629.4  693.74   649.1  691.39   688.4  682.49
   727.7  690.27   747.4  690.36   776.7  683.35   805.9  680.21   874.1  655.31
     913  645.36   971.4  637.12   990.9   631.5  1010.4   630.7  1068.8  630.93
  1078.6  632.52  1088.3  636.98  1117.5   656.2  1195.4  685.46  1253.8  715.97
  1351.2  750.52  1477.7  779.75  1526.3  796.38  1672.3  838.07  1915.5  915.12
#Mann= 3 , 0 , 0
       0      .1       0   971.4    .045       0  1088.3      .1       0
Bank Sta=971.4,1088.3
XS Rating Curve= 0 ,0
Exp/Cntr=0.3,0.1

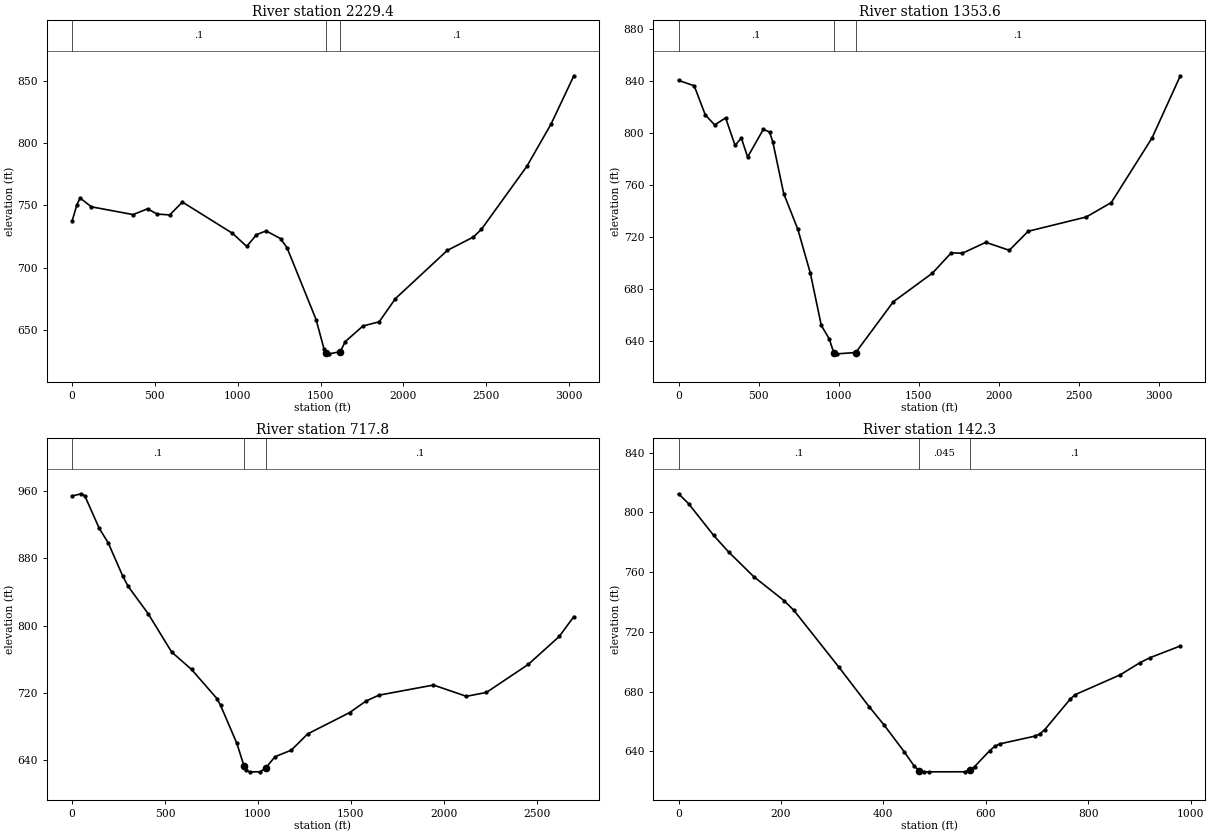
Type RM Length L Ch R = 1 ,2229.4  ,907.6,875.8,843.9
XS GIS Cut Line= 6
     1890336.265      695355.736     1890387.884      695808.624
      1890340.48      696013.459     1889862.328      696477.436
      1889821.35      696895.415     1890857.808      697634.999
#Sta/Elev= 30
       0  737.36    29.1  750.46    48.5  755.97   116.4  748.88   368.5  742.62
   455.8  747.28   513.2  743.05   589.6  742.34   666.1   752.7   967.4  727.68
  1054.9  717.06  1113.3  726.47  1171.5  729.53  1258.8  723.29  1297.6  716.05
  1473.1  658.29    1522  634.25  1531.7  631.51  1551.2   630.7  1619.6  632.42
  1648.9  640.49  1756.4  653.09  1854.3  656.47  1952.2  675.08  2265.7  713.86
  2422.4  724.53  2471.4  730.77  2745.6  781.38  2892.5  815.54  3029.6   854.2
#Mann= 3 , 0 , 0
       0      .1       0  1531.7    .045       0  1619.6      .1       0
Bank Sta=1531.7,1619.6
XS Rating Curve= 0 ,0
Exp/Cntr=0.3,0.1

Type RM Length L Ch R = 1 ,1353.6  ,645.8,635.8,625.4
XS GIS Cut Line= 4
     1888117.515      696164.764     1888706.766      696588.124
     1889435.933      696810.346     1890838.711      697671.457
#Sta/Elev= 30
       0  840.49      98  836.34   166.7  814.03   225.5  806.21   294.2  811.63
     353  790.48   392.2  796.19   431.4   781.5   529.5  802.82   568.7  800.74
   588.3  793.38   656.9  753.42   745.1  725.92   823.3   692.1   891.7  651.93
   940.6  641.76   969.9  630.84   989.4   630.1  1106.7  631.09  1341.2  670.14
  1585.8  692.21  1703.4  707.86    1772  707.46  1918.9  715.88  2065.9  709.78
  2183.5  724.41    2546  735.39  2702.8   746.5  2957.5  796.29  3133.8  844.04
#Mann= 3 , 0 , 0
       0      .1       0   969.9    .045       0  1106.7      .1       0
Bank Sta=969.9,1106.7
XS Rating Curve= 0 ,0
Exp/Cntr=0.3,0.1

Type RM Length L Ch R = 1 ,717.8   ,580,575.6,571.1
XS GIS Cut Line= 4
     1888248.433      697039.512     1888873.433      697312.082
      1889446.35      697187.082     1890776.211      697720.068
#Sta/Elev= 30
       0  953.91    48.7  956.58    68.2  954.38   146.1  915.59   194.8  898.13
   272.7   858.8     302  846.53   409.1  814.26   535.7  768.64   642.9  747.88
   779.6  713.31   799.1  705.29   887.1  659.96   926.2  632.56     936  627.87
   955.5   626.2  1014.1  626.24  1043.5  631.16  1092.3  644.15  1180.3     652
  1268.2  671.27  1493.9  696.58  1582.3  710.32    1651  717.27  1945.3  729.32
    2122  715.96  2229.9   720.5  2455.6  753.86  2622.4  787.09  2700.9  810.69
#Mann= 3 , 0 , 0
       0      .1       0   926.2    .045       0  1043.5      .1       0
Bank Sta=926.2,1043.5
XS Rating Curve= 0 ,0
Exp/Cntr=0.3,0.1

Type RM Length L Ch R = 1 ,142.3   ,148.5,142.3,136.1
XS GIS Cut Line= 2
     1889036.952      697913.613     1889935.389      697522.988
#Sta/Elev= 30
       0  812.54    19.6   805.9    68.6  784.64      98  773.48     147  756.97
   205.7  741.01   225.3   734.4   313.5  696.18   372.3  669.81   401.7  657.43
   440.9  639.52   460.4  629.92   470.2  627.02     480  626.23   489.8   626.2
   558.4  626.24   568.2  627.21     578  629.71   607.4  640.33   617.2  643.23
     627  644.92   695.6  650.11   705.4  651.59   715.2  654.54   764.2  674.72
     774  677.85   862.1  691.17   901.3  699.42   920.9  702.75   979.7  710.55
#Mann= 3 , 0 , 0
       0      .1       0   470.2    .045       0   568.2      .1       0
Bank Sta=470.2,568.2
XS Rating Curve= 0 ,0
Exp/Cntr=0.3,0.1

Chan Stop Cuts=-1
Use User Specified Reach Order=0
Composite Channel Slope=5